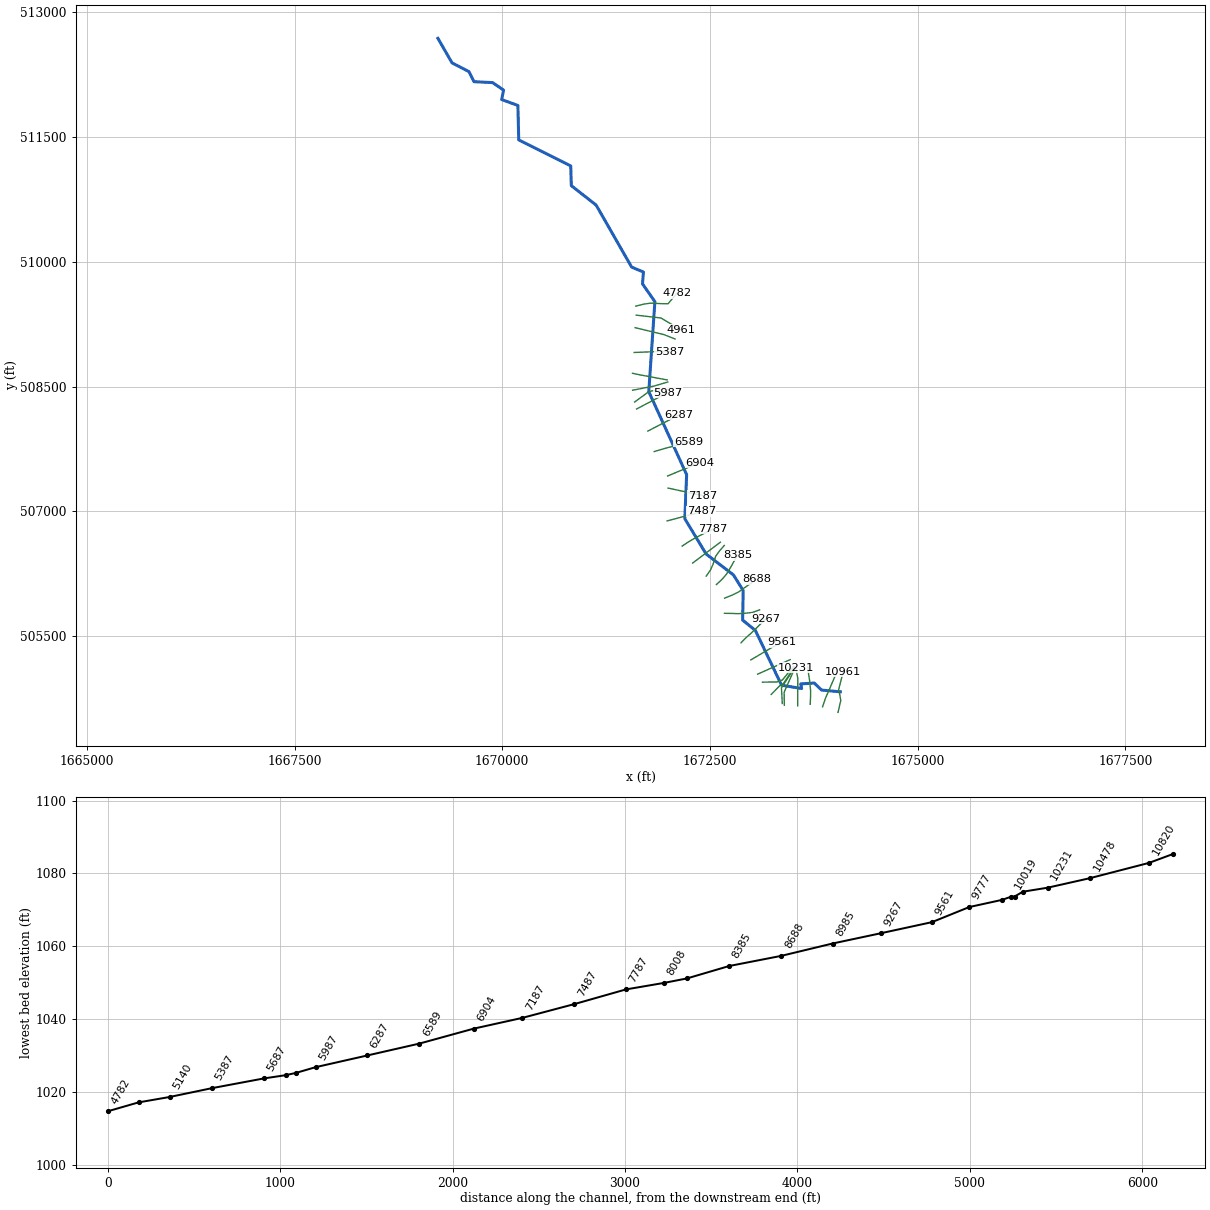
--- WilliamsRn.prj (project) ---

Proj Title=WilliamsRn
Current Plan=p01
Default Exp/Contr=0,0
English Units
Geom File=g01
Flow File=f01
Plan File=p01
BEGIN DESCRIPTION:
---------- MODELED AS PART OF WVEM CTP PROGRAM, 2025----------
Stream Name: Williams Run
Flood Zone: AFH
Marshall County, WV
HEC-RAS Version: RAS 6.6
Vertical Datum: NAVD88
Projection: NAD 1983 StatePlane West Virginia N FIPS 4701 (US Feet)
Terrain: 1-meter West Virginia FEMA R3 South Central (collected 2018-2019)
Land Use: 2024 NLCD
Hydrologic Method:
Duda et al., "Estimation of magnitude and frequency of floods for rural, unregulated streams in and near Virginia and West Virginia." September 8, 2025.
Additional Model Notes:
Coincident peak modeled as normal depth
END DESCRIPTION:
DSS Export Rating Curves= 0
DSS Export Rating Curve Sorted= 0
DSS Export Volume Flow Curves= 0
DXF OffsetX= 0
DXF OffsetY= 0
DXF ScaleX= 0
DXF ScaleY= 0

--- WilliamsRn.p01 (plan) ---

Plan Title=Floodplain
Program Version=6.60
Short Identifier=Floodplain
Geom File=g01
Flow File=f01
Subcritical Flow
K Sum by GR= 0
Std Step Tol= 0.01
Critical Tol= 0.01
Num of Std Step Trials= 20
Max Error Tol= 0.3
Flow Tol Ratio= 0.001
Split Flow NTrial= 30
Split Flow Tol= 0.02
Split Flow Ratio= 0.02
Log Output Level= 0
Friction Slope Method= 1
Unsteady Friction Slope Method= 2
Unsteady Bridges Friction Slope Method= 1
Parabolic Critical Depth
Global Vel Dist= 0 , 0 , 0
Global Log Level= 0
CheckData=False
Encroach Param=-1 ,0,0, 0
Flow Ratio Tolerance=0.1
Flow Ratio Min Ratio=0.5
Flow Ratio Max Ratio=4
Flow Ratio Max Iterations= 10
Mapping Interval=1HOUR
Computation Time Step Use Courant=        0
Computation Time Step Use Time Series=    0
Computation Time Step Count To Double=0
Computation Time Step Max Doubling=0
Computation Time Step Max Halving=0
Computation Time Step Residence Courant=0
Run HTab= 0
Run UNet= 0
Run Sediment= 0
Run PostProcess= 0
Run WQNet= 0
Run RASMapper=-1
UNET Theta= 0
UNET Theta Warmup= 0
UNET ZTol= 0
UNET ZSATol= 0
UNET MxIter= 0
UNET Max Iter WO Improvement= 0
UNET MaxInSteps= 0
UNET DtIC= 0
UNET DtMin= 0
UNET MaxCRTS= 0
UNET WFStab= 0
UNET SFStab= 0
UNET WFX= 1
UNET SFX= 1
UNET Gravity=32.17405
UNET 1D Methodology=Finite Difference
UNET DSS MLevel= 1
UNET Pardiso=0
UNET DZMax Abort= 0
UNET Use Existing IB Tables= 0
UNET Froude Reduction=False
UNET Froude Limit= 0
UNET Froude Power= 0
UNET D1 Cores= 0
UNET WindReference=Eulerian
UNET WindDragFormulation=Hsu (1988)
UNET D2 Coriolis=0
UNET D2 Cores= 0
UNET D2 Theta= 1
UNET D2 Theta Warmup= 1
UNET D2 Z Tol= 0.01
UNET D2 Volume Tol= 0.01
UNET D2 Max Iterations= 20
UNET D2 Advanced Convergence=0
UNET D2 WS Max Tol=0.15
UNET D2 WS RMS Tol=0.002
UNET D2 WS Stall Tol=1
UNET D2 Equation= 0
UNET D2 RampUpFraction=0.1
UNET D2 TimeSlices= 1
UNET D2 Turbulence Formulation=Non-Conservative (original)
UNET D2 Eddy Viscosity=0.3
UNET D2 Transverse Eddy Viscosity=0.1
UNET D2 Smagorinsky Mixing=0
UNET D2 BCVolumeCheck=0
UNET D2 Cores=0
UNET D2 SolverType=PARDISO (Direct)
UNET D2 Minimum Iterations= 3
UNET D2 Maximum Iterations= 30
UNET D2 Restart Number= 10
UNET D2 Relaxation Coeff=1.3
UNET D2 SOR Precondition Iterations= 10
UNET D2 ILUT Maximum Fill= 8
UNET D2 ILUT Tolerance=1E-08
UNET D2 Convergence Tolerance=0.00001
PS Theta= 1
PS WS Tol= 0.01
PS Volume Tol= 0.01
PS Max Iterations= 20
PS Equation= 0
PS Advance Time Step=-1
PS Target Courant=0.9
PS Time Slices= 1
PS Iterate With 2D=0
PS Project Initial WSE from DS=-1
PS Ramp Up Initial WSE from US=-1
PS Cores=0
UNET D1D2 MaxIter= 0
UNET D1D2 ZTol=0.01
UNET D1D2 QTol=0.1
UNET D1D2 MinQTol=1
Write IC File= 0
Write IC File at Fixed DateTime=0
Write IC File at Sim End=0
Echo Input=False
Echo Parameters=False
Echo Output=False
Write Detailed= 0
HDF Write Warmup=0
HDF Write Time Slices=0
HDF Flush=0
HDF Compression= 1
HDF Chunk Size= 1
HDF Spatial Parts= 1
HDF Use Max Rows=0
HDF Fixed Rows= 1
Calibration Method= 0
Calibration Iterations= 20
Calibration Max Change=0.05
Calibration Tolerance=0.2
Calibration Maximum=1.5
Calibration Minimum=0.5
Calibration Optimization Method= 1
WQ AD Non Conservative
WQ ULTIMATE=-1
WQ Max Comp Step=1HOUR
WQ Output Interval=15MIN
WQ Output Selected Increments= 0
WQ Create Restart=0
WQ Fixed Restart=0
WQ System Summary=0
WQ Write To DSS=0
Sorting and Armoring Iterations= 10
XS Update Threshold= 0.02
Bed Roughness Predictor= 0
Processes Affected by Predictor=Sediment Only
Hydraulics Update Threshold= 0.02
Energy Slope Method= 1
Volume Change Method= 1
Sediment Retention Method= 0
Sediment TS Multiplier= 1
Warm Up Method= 0
XS Weighting Method= 0
Number of US Weighted Cross Sections= 1
Number of DS Weighted Cross Sections= 1
Upstream XS Weight=0
Main XS Weight=1
Downstream XS Weight=0
Number of DS XS's Weighted with US Boundary= 1
Upstream Boundary Weight= 1
Weight of XSs Associated with US Boundary= 0
Number of US XS's Weighted with DS Boundary= 1
Downstream Boundary Weight= 0.5
Weight of XSs Associated with DS Boundary= 0.5
Percentile Method= 0
Sediment Output Level= 3
Mass or Volume Output= 0
Output Increment Type= 1
Profile and TS Output Increment= 1
Transport Output Increment 1
XS Output Flag= 0
XS Output Increment= 10
Read HDF5 Sediment Hotstart= 0
Sediment Hotstart Type= 0
Write Gradation File= 0
Read Gradation Hotstart= 0
Write HDF5 File= 1
Write Binary Output= 1
Write DSS Sediment File= 0
DSS Sediment Output Type= 1
SV Curve= 0
Specific Gage Flag= 0
Subcell Erosion Methods= 0
Subcell Deposition Methods= 0
Advection Scheme= 1
Matrix Solver= 0
Implicit Weighting Factor= 1
Maximum Outer Loop Convergence Iterations= 5
Convergence Maximum Absolute= 0.001
Convergence RMSE= 0.0001
Grain Fractions Max Abs Error= 0.001
Max Subgrid Regions= 1
Max Subgrid Length Scale= 3.402823E+38
Initial Layer Thickness= 3
Min Layer Thickness= 0.1
Max Layer Thickness= 6
Number of Layers= 5

--- WilliamsRn.f01 (steady flow) ---

Flow Title=Flow
Program Version=6.60
Number of Profiles= 1
Profile Names=P100yr
River Rch & RM=WilliamsRn,Main,10961
     715
River Rch & RM=WilliamsRn,Main,10088
     977
River Rch & RM=WilliamsRn,Main,7487
    1060
River Rch & RM=WilliamsRn,Main,5687
    1330
River Rch & RM=WilliamsRn,Main,4782
    1480
Boundary for River Rch & Prof#=WilliamsRn,Main            , 1
Up Type= 0
Dn Type= 3
Dn Slope=0.008148
DSS Import GetInterval= 0
DSS Import GetPeak= 0
DSS Import FillOption= 0

--- WilliamsRn.g01 (geometry) ---

Geom Title=Geometry
Program Version=6.60

River Reach=WilliamsRn      ,Main
Reach XY= 30
     1674069.402      504829.321     1673843.842      504850.076
     1673755.619      504934.916     1673592.706      504924.506
     1673603.376      504868.814     1673362.128      504908.891
     1673046.453      505567.743     1672893.617       505691.79
     1672900.209      506047.205     1672783.165      506234.943
     1672454.132      506486.499     1672197.495      506911.174
     1672219.535      507441.028     1671763.894      508439.791
      1671837.35      509522.117     1671688.374      509735.403
     1671699.478      509877.439     1671557.442      509937.584
     1671130.224      510683.052     1670831.213      510917.409
     1670824.591      511153.914     1670198.672      511467.538
     1670188.435      511881.676     1669993.656         511952.
     1670016.146      512066.146     1669884.375       512156.51
     1669660.156      512167.188     1669599.479      512288.281
     1669395.752      512393.392     1669225.885      512689.319

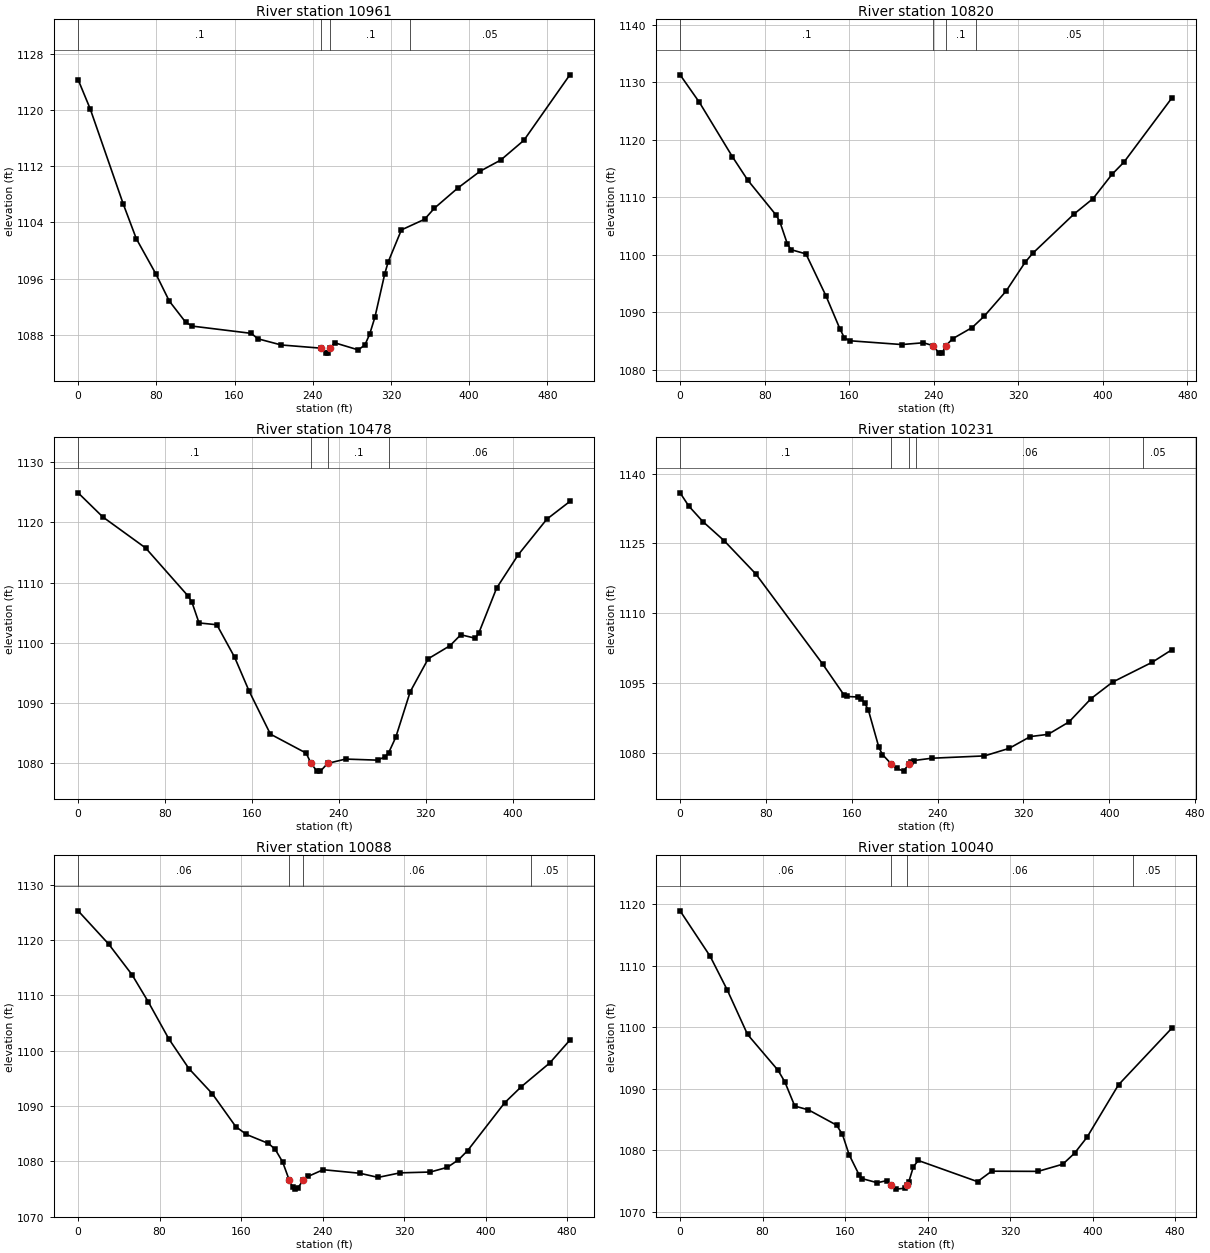
Type RM Length L Ch R = 1 ,10961   ,146,141.7,138.1
XS GIS Cut Line= 5
1674041.34141576 504581.407956851674074.89298812504724.707190878
1674059.44203286504813.547844497 1674045.7333854504843.021436542
1674103.47067246505068.763168227
#Sta/Elev= 30
       0 1124.28    12.4 1120.11    46.1 1106.62    59.5 1101.67    79.8 1096.59
    93.2 1092.81   110.1 1089.77   116.8 1089.24   177.1 1088.21   183.8 1087.44
   207.7 1086.56   247.9 1086.11   253.5  1085.4   255.1 1085.42   257.9 1086.11
   262.4 1086.87   286.5 1085.86   293.3 1086.57   298.1 1088.07   303.5 1090.49
   313.6 1096.68     317 1098.33   330.6 1102.92   354.3 1104.43   364.4 1106.01
   388.1 1108.85   411.3 1111.28   432.2 1112.85   455.9 1115.66   502.9 1124.97
#Mann= 4 ,-1,0
       0      .1       0   247.9    .045       0   257.9      .1       0
  339.85     .05       0
Bank Sta=247.9,257.9
XS Rating Curve= 0 ,0
Exp/Cntr=0.3,0.1

Type RM Length L Ch R = 1 ,10820   ,331.8,342,338.8
XS GIS Cut Line= 3
1673855.69708961504648.2698753691673890.84925968504752.046575604
1674032.14329786505078.513516273
#Sta/Elev= 30
       0 1131.26    18.3 1126.47    49.5 1117.03      64 1112.97    91.1 1106.83
    94.5 1105.68   101.5 1101.88   104.9 1100.89   119.1 1100.15     138 1092.87
   151.2 1087.14   155.5 1085.55   160.5 1085.06   209.8  1084.4   230.3 1084.71
  238.851084.235   245.3 1082.91   247.8 1082.93  251.721084.235   257.8  1085.4
   276.4 1087.36   287.7 1089.31   308.5 1093.69   326.4 1098.67   333.6 1100.24
   372.9  1107.1   390.8 1109.76   408.6 1113.95     420 1116.09   465.3 1127.23
#Mann= 4 ,-1,0
       0      .1       0  238.85    .045       0  251.72      .1       0
  279.57     .05       0
Bank Sta=238.85,251.72
XS Rating Curve= 0 ,0
Exp/Cntr(USF)=0,0
Exp/Cntr=0.3,0.1

Type RM Length L Ch R = 1 ,10478   ,243.4,246.4,239.5
XS GIS Cut Line= 6
1673706.80993451504679.0693515841673711.11045083504773.256499171
 1673711.0894535504848.8459149151673701.16558884504954.766634837
1673687.93989351505036.866208166 1673677.7784965  505129.5445005
#Sta/Elev= 30
       0 1124.88    22.7 1120.88    62.1 1115.74   101.5 1107.71   104.8 1106.72
   111.3  1103.3   127.7    1103   144.1  1097.6   157.3 1092.04     177 1084.86
   209.9 1081.71  214.471079.993   219.8 1078.73   223.1 1078.72  229.621079.994
   246.2 1080.72   275.8 1080.54   282.5  1081.1   285.9 1081.78   292.4 1084.32
   305.7 1091.88   322.3 1097.36   342.3 1099.52   352.3 1101.34   365.5 1100.77
   368.8 1101.59   385.3 1109.09   405.1 1114.59   431.5 1120.51   452.7 1123.45
#Mann= 4 ,-1,0
       0      .1       0  214.47    .045       0  229.62      .1       0
  286.26     .06       0
Bank Sta=214.47,229.62
XS Rating Curve= 0 ,0
Exp/Cntr(USF)=0,0
Exp/Cntr=0.3,0.1

Type RM Length L Ch R = 1 ,10231   ,145.3,143.3,139.5
XS GIS Cut Line= 3
1673555.98396354 504660.760242111673557.39314488 504992.62342903
1673533.61867984505116.778449923
#Sta/Elev= 30
       0 1135.86     8.1 1133.02    21.3 1129.67      41 1125.59    70.5 1118.46
   132.8 1099.11   152.5 1092.54   155.8 1092.12   165.6 1092.01   168.9  1091.6
   172.2 1090.63   175.5 1089.19   185.3 1081.17   188.6 1079.65     197 1077.59
   201.7  1076.7   208.3 1076.09  212.95 1077.55   214.8 1078.06   218.1 1078.37
   234.5 1078.86   283.7 1079.36   306.7 1080.98   326.4 1083.51     343 1083.99
   362.5 1086.66   383.1 1091.68   403.1 1095.21   439.9 1099.46   458.3 1102.15
#Mann= 5 ,-1,0
       0      .1       0     197    .045       0  212.95      .1       0
     220     .06       0  431.87     .05       0
Bank Sta=197,212.95
XS Rating Curve= 0 ,0
Exp/Cntr(USF)=0,0
Exp/Cntr=0.3,0.1

Type RM Length L Ch R = 1 ,10088   ,49,47.6,46.5
XS GIS Cut Line= 3
1673395.43907248504668.5296096011673392.78524134 504823.33642636
1673525.47679856505123.219345683
#Sta/Elev= 30
       0 1125.29    29.9  1119.3      53 1113.72    68.9 1108.83      89 1102.16
   108.7 1096.79   131.6 1092.26   154.8 1086.28   165.3 1084.87   186.9 1083.24
   193.4 1082.21   200.8  1079.9  207.331076.591   210.8 1075.29   213.2 1074.99
   215.6 1075.19  221.011076.589   225.7 1077.28   240.6  1078.5   276.6 1077.86
   294.5 1077.11     316 1077.93   345.8 1078.08   362.5 1078.93   373.4 1080.28
   382.4 1081.95   418.8  1090.6     435 1093.48   463.1  1097.8   482.8 1101.92
#Mann= 4 ,-1,0
       0     .06       0  207.33    .045       0  221.01     .06       0
  444.83     .05       0
Bank Sta=207.33,221.01
XS Rating Curve= 0 ,0
Exp/Cntr(USF)=0,0
Exp/Cntr=0.3,0.1

Type RM Length L Ch R = 1 ,10040   ,25.3,21.3,18.3
XS GIS Cut Line= 3
1673370.86594154504688.9296254891673360.73471883504877.847131355
  1673518.066648505118.612659336
#Sta/Elev= 30
       0 1118.97    29.2 1111.56    45.7  1106.1    65.4 1098.85    94.9 1093.03
   101.5 1091.15   111.2 1087.19   124.5 1086.57   151.7 1084.09   157.4 1082.59
   163.9 1079.28   173.6 1075.98   176.7 1075.37   191.2 1074.71   200.2 1075.05
  204.61 1074.32   209.7 1073.67   217.9 1073.82  219.85 1074.32   221.8 1074.89
   226.3 1077.35     231 1078.33   288.4 1074.89   302.1 1076.59   347.1 1076.56
   371.1 1077.73   382.5 1079.52   394.6 1082.12   425.1 1090.65   476.8 1099.87
#Mann= 4 ,-1,0
       0     .06       0  204.61    .045       0  219.85     .06       0
  439.19     .05       0
Bank Sta=204.61,219.85
XS Rating Curve= 0 ,0
Exp/Cntr(USF)=0,0
Exp/Cntr=0.3,0.1

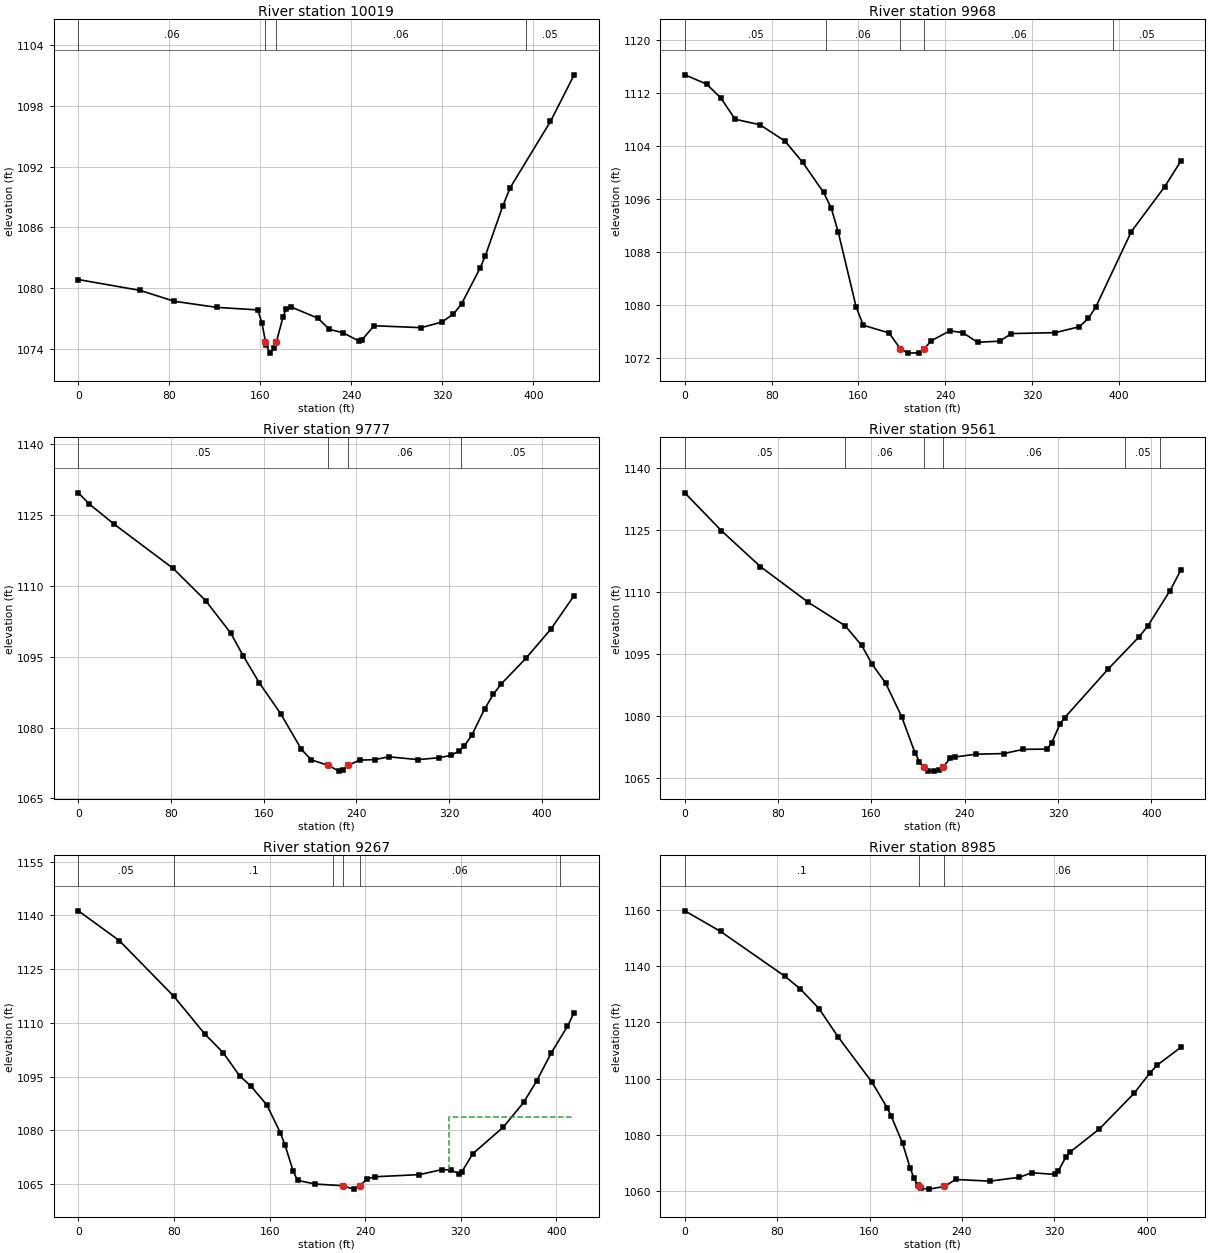
Type RM Length L Ch R = 1 ,10019   ,51.7,50.6,50.4
XS GIS Cut Line= 4
1673237.00286373504797.5218664241673344.41884663504906.451019991
1673380.84300119504923.2973994681673514.41916879505125.873176827
#Sta/Elev= 30
       0 1080.86    54.4 1079.79    84.3 1078.72   121.7 1078.12   157.7 1077.87
   161.3 1076.61   164.5 1074.75   165.1  1074.4   168.5 1073.61   172.1  1074.1
  174.14 1074.74   179.9 1077.17   182.4 1077.92   186.6 1078.18   210.6 1077.05
   220.7 1075.95   232.6 1075.62   246.8 1074.79   249.1 1074.88   259.9 1076.31
   301.2 1076.12   319.5 1076.67   329.7 1077.46   336.8 1078.46   353.3 1082.03
   357.7  1083.2   373.1 1088.12   379.6 1089.92     415 1096.45   435.8 1101.04
#Mann= 4 ,-1,0
       0     .06       0   164.5    .045       0  174.14     .06       0
  393.11     .05       0
Bank Sta=164.5,174.14
XS Rating Curve= 0 ,0
Exp/Cntr(USF)=0,0
Exp/Cntr=0.3,0.1

Type RM Length L Ch R = 1 ,9968    ,189.2,191,190.3
XS GIS Cut Line= 4
 1673131.8251788504945.4126590051673307.86264471504948.066490149
1673372.43920256504971.9509704491673506.01537016505136.488501405
#Sta/Elev= 30
       0 1114.75      20 1113.36    33.1 1111.29    46.3 1108.05    69.2 1107.22
    92.2 1104.77   108.6 1101.55   127.9    1097   134.9 1094.65   141.4    1091
   157.8 1079.76   164.4 1076.97   188.1 1075.81   198.6 1073.41   205.6 1072.76
   216.1 1072.81  220.77 1073.42   226.6 1074.58   244.1 1076.12     256 1075.86
   269.7  1074.4   290.1 1074.56   300.9 1075.71   341.4 1075.85   363.4 1076.74
   371.8 1077.99   378.8 1079.77   411.4  1091.1     442 1097.84   456.8 1101.68
#Mann= 5 ,-1,0
       0     .05       0     130     .06       0   198.6    .045       0
  220.77     .06       0  394.91     .05       0
Bank Sta=198.6,220.77
XS Rating Curve= 0 ,0
Exp/Cntr(USF)=0,0
Exp/Cntr=0.3,0.1

Type RM Length L Ch R = 1 ,9777    ,214.9,216.4,216.8
XS GIS Cut Line= 2
  1673074.325504505041.8351905861673465.32329262505216.103435738
#Sta/Elev= 30
       0  1129.7     9.4 1127.34      31 1123.05    81.9 1113.69     110 1106.85
   131.6    1100   142.3 1095.21   156.4 1089.42   174.7 1082.94   192.6 1075.39
   201.1 1073.17  215.791071.991     225 1070.78   228.5 1071.09  232.921071.991
   242.9 1073.11   255.8 1073.21   268.1 1073.81   293.1 1073.22   311.2 1073.61
   321.9 1074.12   329.1 1075.11   333.1 1076.02   339.9 1078.48   350.7 1083.89
   358.3 1087.05     365  1089.2   386.6 1094.71   408.1 1100.88   428.1 1107.96
#Mann= 4 ,-1,0
       0     .05       0  215.79    .045       0  232.92     .06       0
     330     .05       0
Bank Sta=215.79,232.92
XS Rating Curve= 0 ,0
Exp/Cntr(USF)=0,0
Exp/Cntr=0.3,0.1

Type RM Length L Ch R = 1 ,9561    ,291.4,294.6,295.3
XS GIS Cut Line= 6
1672991.59372945505212.7752996741673067.01385421 505257.13839992
1673131.65873803505295.1645705911673217.85213521505345.866897008
1673283.46978613505382.2401838361673360.48308353505423.904798662
#Sta/Elev= 30
       0 1133.95    31.3 1124.81    64.9 1116.09     106 1107.44   137.4 1101.81
   151.7 1097.03   160.7 1092.44   172.1 1087.99   185.9 1079.82   197.3  1071.1
   201.1 1068.94   204.9 1067.53   208.7 1066.72   213.5 1066.63   218.3 1066.86
   221.5 1067.62   227.8 1069.84   231.6 1070.05   249.4 1070.72   273.5 1070.88
   290.3  1071.9   310.8 1071.96   314.6 1073.52   321.7 1078.04   325.8  1079.6
   362.8 1091.27   389.7 1099.19   396.8 1101.67   416.1 1110.32   425.1 1115.17
#Mann= 6 ,-1,0
       0     .05       0   137.5     .06       0   204.9    .045       0
   221.5     .06       0  377.52     .05       0  407.52      .1       0
Bank Sta=204.9,221.5
XS Rating Curve= 0 ,0
Exp/Cntr(USF)=0,0
Exp/Cntr=0.3,0.1

Type RM Length L Ch R = 1 ,9267    ,287.5,281.7,272.7
XS GIS Cut Line= 4
1672874.12459201505418.523581341 1672938.4846995505484.964721426
1672999.36154626505537.5610729161673172.28042279505706.712623769
#Sta/Elev= 30
       0 1141.28    34.3 1132.96      80 1117.38   105.6 1106.98   121.1 1101.71
   135.1 1095.15   144.4 1092.35   157.7  1087.1   169.1 1079.27     173 1075.83
   179.7 1068.64   183.4 1066.06   198.1 1065.02     221 1064.56   230.3  1063.6
  235.57 1064.57   241.9 1066.51   248.6 1067.06   285.3 1067.65   304.5 1069.07
   311.5 1068.93   318.4 1067.93   320.8 1068.39     330 1073.48   355.6 1080.93
   372.5  1087.8   383.4 1093.76   395.4 1101.49   409.2 1109.05   414.8 1112.89
#Mann= 6 ,-1,0
       0     .05       0      80      .1       0  212.95     .06       0
     221    .045       0  235.57     .06       0  402.95      .1       0
#XS Ineff= 2 , 0
                          310.06         1083.86
Permanent Ineff=
       F       F
Bank Sta=221,235.57
XS Rating Curve= 0 ,0
Exp/Cntr(USF)=0,0
Exp/Cntr=0.3,0.1

Type RM Length L Ch R = 1 ,8985    ,291.5,297.2,300.5
XS GIS Cut Line= 6
1672674.65156576505773.127202839  1672763.183869505772.016968846
   1672838.94356505769.2069350931672938.77210051 505775.88572751
1673013.31394617505784.1658946721673097.96272701505815.101528332
#Sta/Elev= 30
       0 1159.63      31  1152.3    86.8 1136.36    99.9 1131.93   116.3 1124.88
   132.7  1114.9   162.3 1098.66   175.4 1089.57   178.7  1086.8   188.6 1077.09
   195.2 1068.29   198.5  1064.6   201.7 1062.12  202.911061.724     205 1061.04
   211.6 1060.76  224.911061.723   234.6 1064.19   264.2  1063.6   289.8 1064.96
   300.5 1066.58   320.3 1065.99   323.6  1067.3   330.2 1072.19   333.5 1073.85
   359.1 1082.13   389.1 1094.76   403.1 1102.14   409.2 1104.81   429.5 1111.09
#Mann= 3 ,-1,0
       0      .1       0  202.91    .045       0  224.91     .06       0
Bank Sta=202.91,224.91
XS Rating Curve= 0 ,0
Exp/Cntr(USF)=0,0
Exp/Cntr=0.3,0.1

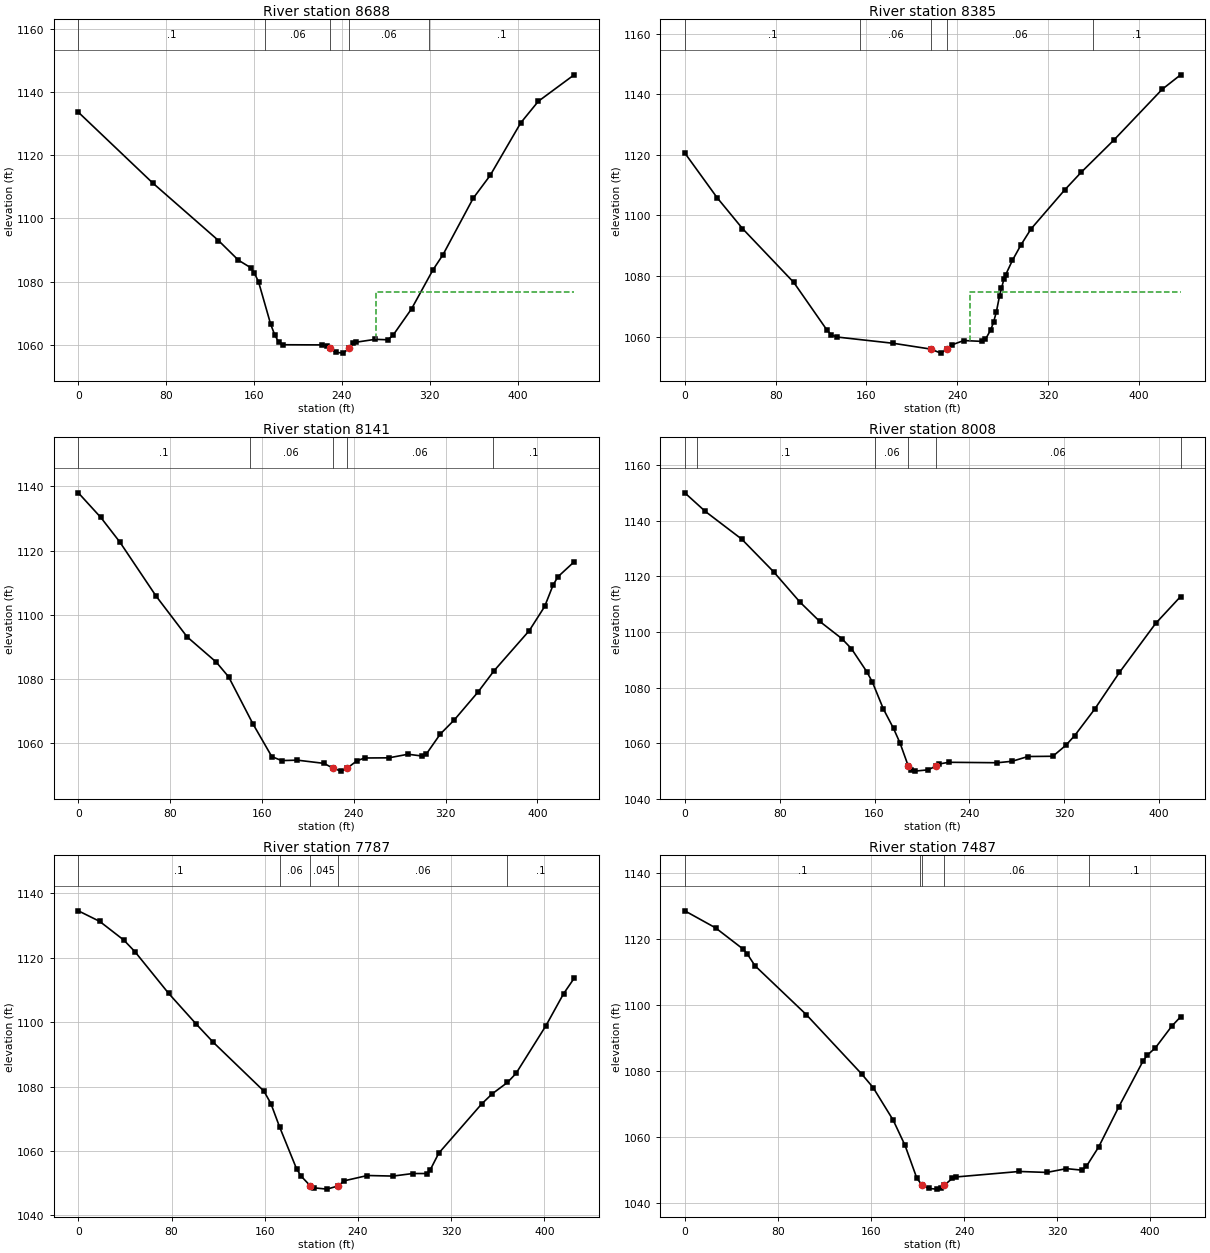
Type RM Length L Ch R = 1 ,8688    ,297.9,302.3,303.8
XS GIS Cut Line= 6
1672676.77164026505955.8807743341672769.48602176505993.372169167
1672847.70404117506031.6220926791672930.49915117506091.122629836
1672991.94161358506134.1320582631673063.79645675506184.064373091
#Sta/Elev= 30
       0 1133.58    67.6 1111.23   127.6 1092.99   145.8 1086.76   156.8 1084.43
   160.4 1082.63   164.1 1079.93     175 1066.68   178.7 1063.24   182.3 1060.95
     186 1060.02   222.2 1059.97   226.3  1059.7  229.251058.944   234.4 1057.64
   241.3 1057.37  246.591058.942   250.5 1060.52   252.5  1060.8   270.2 1061.73
   281.9 1061.59   286.6 1063.04   303.4 1071.36   322.9 1083.69     332 1088.47
   359.6 1106.38     375 1113.57   402.9 1130.23   418.9 1137.04   451.5  1145.4
#Mann= 5 ,-1,0
       0      .1       0  170.01     .06       0  229.25    .045       0
  246.59     .06       0  319.03      .1       0
#XS Ineff= 2 , 0
                          271.06         1076.85
Permanent Ineff=
       F       F
Bank Sta=229.25,246.59
XS Rating Curve= 0 ,0
Exp/Cntr(USF)=0,0
Exp/Cntr=0.3,0.1

Type RM Length L Ch R = 1 ,8385    ,242.6,244.5,244.4
XS GIS Cut Line= 6
1672577.71311134506119.3384526671672647.15949476506183.546985671
 1672698.3316365506243.788991168 1672750.7491826506329.662179008
1672787.65396443506394.9543712591672830.87664701506471.033615425
#Sta/Elev= 30
       0 1120.59    28.5 1105.83    50.8 1095.67      96 1077.89   125.2 1062.19
   129.2 1060.55   134.3 1059.88   183.7 1057.82  216.621055.911   225.5 1054.58
  231.111055.912     235 1057.27   245.7 1058.73   261.9 1058.45   264.8 1059.13
   269.6 1062.37     272 1064.88   274.4 1068.17   277.2 1073.45   278.9 1075.97
     281 1078.89   282.6 1080.42   288.5 1085.14   296.1 1090.29   304.9 1095.53
   334.5 1108.37   349.2 1114.25   377.9 1124.85   420.5 1141.61   436.7 1146.37
#Mann= 5 ,-1,0
       0      .1       0  154.58     .06       0  216.62    .045       0
  231.11     .06       0  359.23      .1       0
#XS Ineff= 2 , 0
                          250.99         1074.72
Permanent Ineff=
       F       F
Bank Sta=216.62,231.11
XS Rating Curve= 0 ,0
Exp/Cntr(USF)=0,0
Exp/Cntr=0.3,0.1

Type RM Length L Ch R = 1 ,8141    ,137.2,133,126.1
XS GIS Cut Line= 6
1672455.24356455506221.1174281341672506.54267455506294.166494633
1672537.11019871506363.0269212231672568.01499255506458.181258465
1672612.67074313506520.8435347181672672.38289404 506588.88572147
#Sta/Elev= 30
       0    1138    19.6 1130.31    36.1 1122.68    67.7 1105.81    94.8 1093.06
   120.2 1085.18     131 1080.57   152.2 1065.89   168.6  1055.7   177.1 1054.46
   190.9 1054.59   214.1 1053.59   221.9  1052.1   228.9 1051.17  234.34  1052.1
   242.7 1054.38   249.5 1055.27   270.7 1055.32   287.3 1056.44   299.4 1055.89
   303.4 1056.57   315.4 1062.72   327.6 1067.13   348.3 1075.84   362.2 1082.44
     393 1095.01   406.4 1102.54   413.7 1109.19   417.9 1111.79   432.1 1116.48
#Mann= 5 ,-1,0
       0      .1       0  149.26     .06       0   221.9    .045       0
  234.34     .06       0   361.6      .1       0
Bank Sta=221.9,234.34
XS Rating Curve= 0 ,0
Exp/Cntr(USF)=0,0
Exp/Cntr=0.3,0.1

Type RM Length L Ch R = 1 ,8008    ,222.5,220.9,218.6
XS GIS Cut Line= 2
1672291.61785007506377.3106714871672625.52288467 506628.81424905
#Sta/Elev= 30
       0 1150.11    17.2 1143.45      48 1133.44    74.8 1121.73    97.2 1110.73
   113.6 1103.89   132.3 1097.67   140.5 1094.01   153.4 1085.74   158.1 1082.05
   167.4 1072.33     176 1065.29   181.5 1060.01   188.5 1051.66   190.9 1050.32
   193.9 1049.94   204.9 1050.39  211.39 1051.65   214.4 1052.51   222.6 1053.12
   263.5 1052.96     276 1053.49   289.3  1055.2   310.3 1055.29   321.2 1059.21
   328.7 1062.72   345.5 1072.21   366.4 1085.44     397 1103.12     418 1112.78
#Mann= 6 ,-1,0
       0     .05       0      10      .1       0     160     .06       0
   188.5    .045       0  211.39     .06       0  418.03      .1       0
Bank Sta=188.5,211.39
XS Rating Curve= 0 ,0
Exp/Cntr(USF)=0,0
Exp/Cntr=0.3,0.1

Type RM Length L Ch R = 1 ,7787    ,299.1,299.9,295.5
XS GIS Cut Line= 6
1672165.50396201506581.9572780881672238.69344817506630.854490012
1672303.46333176506668.8567105831672392.15475543506715.050515845
1672458.89806026506749.2637020051672536.97861275506788.769528508
#Sta/Elev= 30
       0 1134.54    18.3 1131.27    39.1 1125.44    48.6 1121.85    77.5 1108.92
   100.9  1099.5   115.9  1093.7   159.3 1078.57   165.3  1074.7   172.7  1067.5
   187.3 1054.48   191.2 1052.19  199.141049.158     202 1048.56   213.4 1048.15
  223.161049.158   228.2 1050.73   248.2 1052.38   270.1  1052.2     287 1052.99
   299.4 1052.99     302 1054.09   309.4 1059.32   346.2 1074.59   355.3 1077.75
   368.3 1081.25   375.7 1084.07   401.4  1098.9   416.5  1108.8   425.6 1113.61
#Mann= 5 ,-1,0
       0      .1       0  173.12     .06       0  199.14    .045       0
  223.16     .06       0  368.12      .1       0
Bank Sta=199.14,223.16
XS Rating Curve= 0 ,0
Exp/Cntr(USF)=0,0
Exp/Cntr=0.3,0.1

Type RM Length L Ch R = 1 ,7487    ,303.8,300.1,294.8
XS GIS Cut Line= 6
1671984.63588542506884.8192051651672069.20986326506907.257480502
1672141.70217234506926.4903816731672238.39259575506952.004766345
1672311.33306667506969.5460698461672394.52581367507000.280260339
#Sta/Elev= 30
       0  1128.6    26.4 1123.44    50.1 1116.99    53.5 1115.63    60.3 1111.94
   104.4  1097.1     152 1079.08   161.9 1074.93   179.1 1065.07   189.3  1057.4
   199.5 1047.38  204.071045.288   209.6 1044.32   216.4 1044.11   219.8  1044.4
  223.09 1045.29     230  1047.4   233.4 1047.81   287.5 1049.47   311.2 1049.18
     328 1050.33   341.7 1049.86   345.2 1051.03   355.7 1056.87   373.1 1069.12
   394.1 1083.13   397.6 1084.79   404.6 1087.04   418.6 1093.59   426.2 1096.43
#Mann= 5 ,-1,0
       0      .1       0   202.5     .06       0  204.07    .045       0
  223.09     .06       0  347.52      .1       0
Bank Sta=204.07,223.09
XS Rating Curve= 0 ,0
Exp/Cntr(USF)=0,0
Exp/Cntr=0.3,0.1

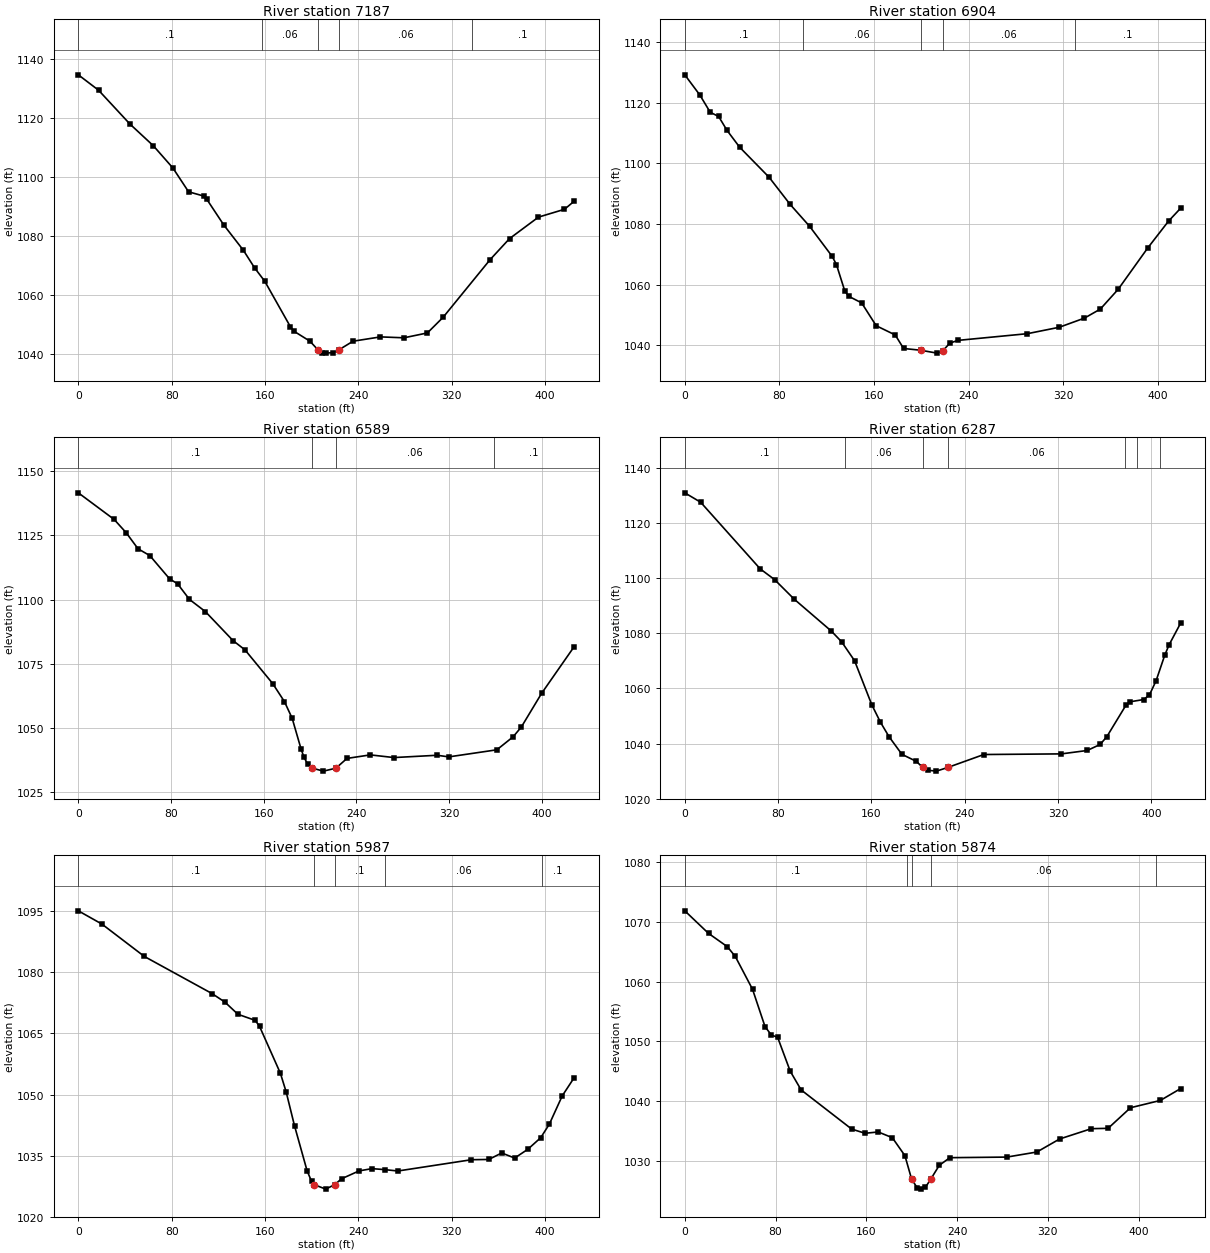
Type RM Length L Ch R = 1 ,7187    ,275.8,283.1,287.3
XS GIS Cut Line= 6
1671996.48166226507279.4719591741672082.01495576507261.023833334
1672155.32878551507245.2112009231672253.08088659507224.127253592
1672326.39504443507208.3146211651672411.92833792507189.866495341
#Sta/Elev= 30
       0 1134.61    17.3 1129.41    44.2 1117.95    64.3 1110.58    81.1 1103.03
    94.5 1094.99   107.3 1093.57   110.1 1092.46   124.7 1083.74   141.5 1075.16
   151.1 1069.21   159.8 1064.69   181.8 1049.26   185.1 1047.69   198.5 1044.39
  205.151041.561   208.6 1040.54     212 1040.34   218.7 1040.52  223.771041.563
   235.5 1044.38     259 1045.84   279.1 1045.53   299.2 1047.18   312.7 1052.49
     353 1072.03   369.6 1079.13   394.4 1086.41   416.7 1089.06     425  1091.8
#Mann= 5 ,-1,0
       0      .1       0   157.5     .06       0  205.15    .045       0
  223.77     .06       0   337.5      .1       0
Bank Sta=205.15,223.77
XS Rating Curve= 0 ,0
Exp/Cntr(USF)=0,0
Exp/Cntr=0.3,0.1

Type RM Length L Ch R = 1 ,6904    ,315,314.5,311.9
XS GIS Cut Line= 2
1671990.26597739507424.8056221831672377.12810592507586.205630735
#Sta/Elev= 30
       0 1129.14    12.7  1122.5    21.5 1116.79    28.6 1115.41    35.7 1110.82
    46.4 1105.26    71.3 1095.35    89.1 1086.39   105.5  1079.2   124.6 1069.27
   128.2 1066.58   135.3 1057.81   138.8 1056.07   149.5 1053.94   161.8 1046.41
   177.9 1043.36     185  1038.9   199.3 1038.33   213.3 1037.37   218.3 1038.22
   224.1 1040.67   230.9 1041.57   289.6 1043.78   316.6  1045.9   337.9 1048.92
   351.3 1051.89   366.4 1058.42   391.4 1072.05     409 1080.91   419.2 1085.15
#Mann= 5 ,-1,0
       0      .1       0     100     .06       0   199.3    .045       0
   218.3     .06       0     330      .1       0
Bank Sta=199.3,218.3
XS Rating Curve= 0 ,0
Exp/Cntr(USF)=0,0
Exp/Cntr=0.3,0.1

Type RM Length L Ch R = 1 ,6589    ,300,302.5,305
XS GIS Cut Line= 6
1671829.52891217507718.8979175841671913.47362617  507743.5865165
1671985.42656626507764.7482195941672082.74756584507788.257358924
1672156.37799601507806.9489225891672239.79646434507838.557127088
#Sta/Elev= 30
       0 1141.59    30.9 1131.23    41.2 1126.11    51.5 1119.82    61.7 1117.15
    78.8 1108.08    85.6  1106.2    95.9 1100.09   109.6 1095.37   133.5 1084.06
   143.8 1080.46   167.7 1067.35   177.8 1060.35   184.5 1053.84   192.1 1041.99
   194.7 1038.64     198 1035.91  201.911034.414   211.5 1033.27  222.221034.413
   231.8 1038.22   251.9 1039.59   272.3 1038.55   309.5 1039.44   319.7 1038.82
   361.1 1041.57   375.1 1046.62   382.2 1050.42   399.7 1063.53   427.8 1081.72
#Mann= 4 ,-1,0
       0      .1       0  201.91    .045       0  222.22     .06       0
  358.59      .1       0
Bank Sta=201.91,222.22
XS Rating Curve= 0 ,0
Exp/Cntr(USF)=0,0
Exp/Cntr=0.3,0.1

Type RM Length L Ch R = 1 ,6287    ,299.7,300,299.9
XS GIS Cut Line= 6
1671752.90734626507965.5066763461671830.63619342508005.687042177
1671897.26138826508040.1269339171671986.09487201508086.046789587
1672052.71973875508120.4866813421672130.44924209   508160.666391
#Sta/Elev= 30
       0 1130.87    13.6 1127.46    64.7 1103.28    76.9 1099.44    93.8 1092.32
   125.6 1080.76   134.4 1076.89   145.5 1070.03   160.3 1054.03   167.7 1047.73
   175.1 1042.46   186.1 1036.09   198.6 1033.51  203.841031.342   208.3 1030.32
   215.7    1030  225.521031.341   256.3 1036.02   322.8 1036.25   344.9 1037.48
     356 1039.66   361.8 1042.52   378.2 1053.94   381.9 1055.15   393.4 1055.95
   398.3 1057.65     404 1062.79   411.4 1072.03   415.1 1075.78     425 1083.64
#Mann= 7 ,-1,0
       0      .1       0   137.5     .06       0  203.84    .045       0
  225.52     .06       0   377.5      .1       0   387.5     .06       0
   407.5      .1       0
Bank Sta=203.84,225.52
XS Rating Curve= 0 ,0
Exp/Cntr(USF)=0,0
Exp/Cntr=0.3,0.1

Type RM Length L Ch R = 1 ,5987    ,113.4,112.9,112.3
XS GIS Cut Line= 6
1671616.79213293508230.497616172 1671694.2217681508271.251471668
1671760.59040175508306.1828322561671849.08136651508352.759182677
1671915.45000017508387.6905432491671992.88029151508428.443414509
#Sta/Elev= 30
       0 1095.08    20.2 1091.83    56.6 1083.88   114.5 1074.79   125.6 1072.69
   136.8 1069.69   151.6  1068.2   155.3 1066.74   173.2 1055.21   178.1 1050.68
   185.3 1042.33   196.1 1031.26   199.9  1028.7  202.141027.877   212.1 1026.78
  219.691027.879   225.7 1029.33   240.6 1031.25   251.7 1031.81   262.5 1031.57
   273.9 1031.23     337    1034   351.8 1034.06   362.9 1035.65     374 1034.41
   385.2 1036.54   396.3 1039.39   403.7 1042.71   414.8 1049.68     425 1054.13
#Mann= 5 ,-1,0
       0      .1       0  202.14    .045       0  219.69      .1       0
   262.5     .06       0   397.5      .1       0
Bank Sta=202.14,219.69
XS Rating Curve= 0 ,0
Exp/Cntr(USF)=0,0
Exp/Cntr=0.3,0.1

Type RM Length L Ch R = 1 ,5874    ,61.8,59.7,58.7
XS GIS Cut Line= 5
1671593.70919318508314.6493686211671743.74265179508424.842756114
1671791.72905339508446.2856793231671896.89237428508462.761327732
1671988.72661049508465.617948599
#Sta/Elev= 30
       0 1071.86    20.9 1068.08    37.5 1065.85    44.5 1064.21    59.7 1058.71
    70.7 1052.46    76.3 1051.04    81.8 1050.67    92.9 1044.99   102.5 1041.85
   147.1 1035.28   158.9 1034.58   170.5  1034.8   182.9 1033.84     194 1030.83
  199.83 1026.94   204.8 1025.43   208.4 1025.22     212  1025.5   216.9 1026.93
   224.3 1029.21   233.6 1030.49   283.8 1030.59   310.3 1031.44   330.3 1033.62
   358.3 1035.35   373.1 1035.41   392.8 1038.86   419.1 1040.08     437 1042.07
#Mann= 5 ,-1,0
       0      .1       0  196.15     .06       0  199.83    .045       0
   216.9     .06       0  415.16      .1       0
Bank Sta=199.83,216.9
XS Rating Curve= 0 ,0
Exp/Cntr(USF)=0,0
Exp/Cntr=0.3,0.1

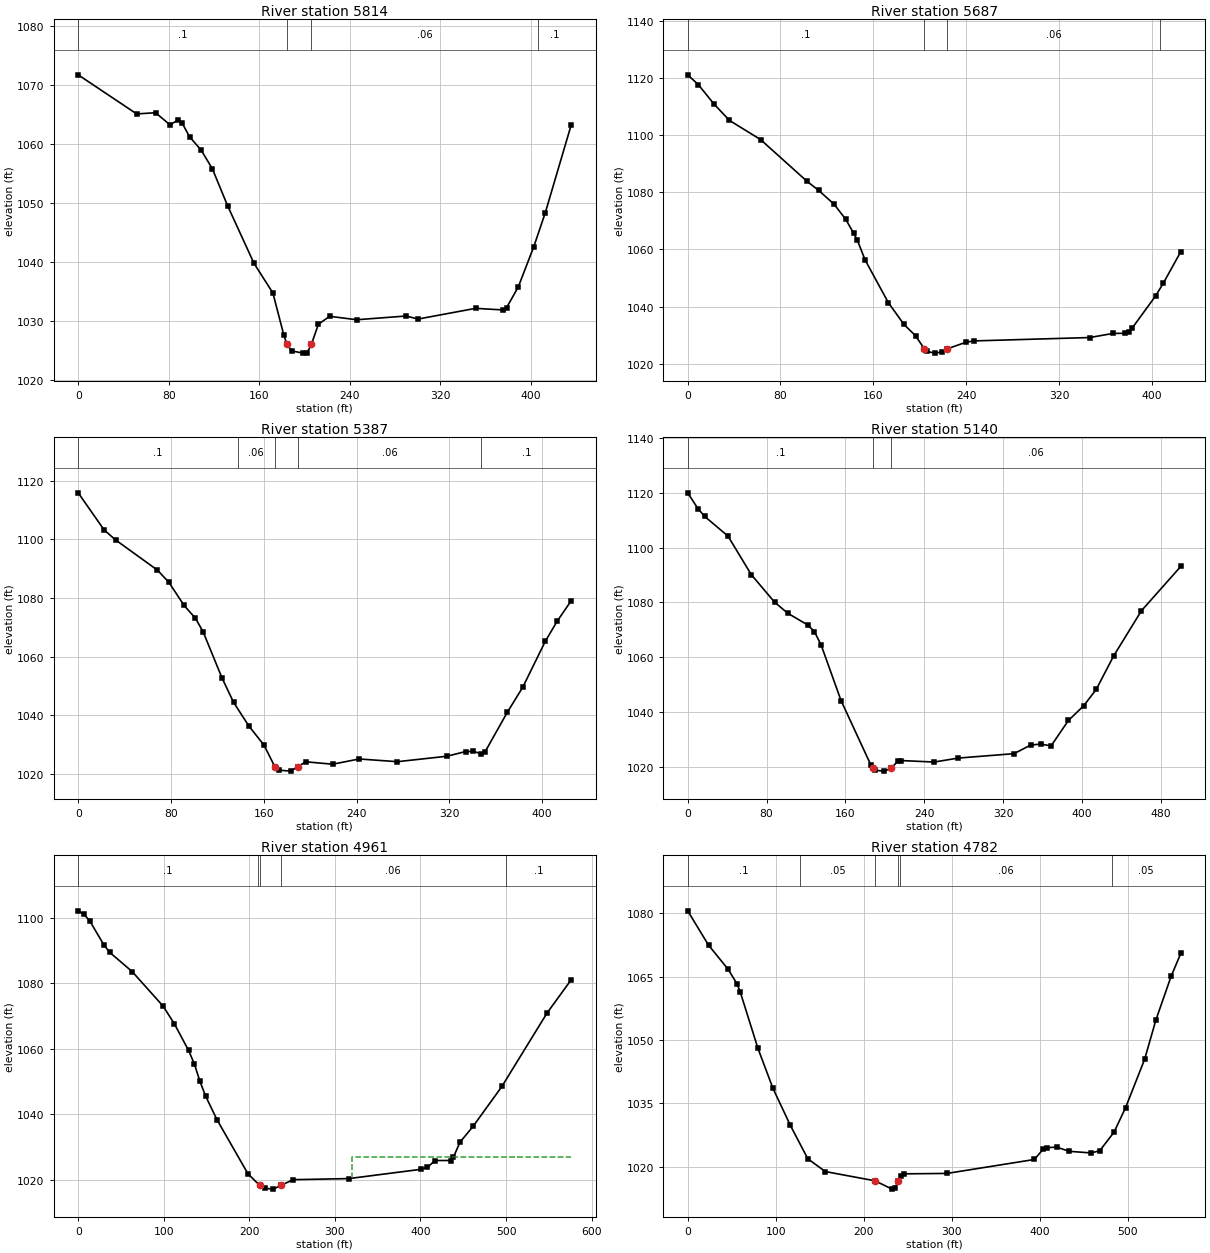
Type RM Length L Ch R = 1 ,5814    ,130.9,127.4,122.9
XS GIS Cut Line= 3
1671569.01940225508456.2985715461671829.97946479508507.605973671
1671992.74777498508555.374934271
#Sta/Elev= 30
       0 1071.69    51.7 1065.07    68.4 1065.28    81.1 1063.22    88.4 1064.08
    91.8 1063.54    98.5 1061.17   108.5 1058.98   118.5  1055.8   131.9 1049.57
   155.3 1039.79     172 1034.77   181.7 1027.61  184.411026.067   188.7 1024.97
   198.5 1024.59   202.1 1024.62  206.021026.069   212.2 1029.49   222.2 1030.82
     246 1030.24   289.6 1030.87   300.3 1030.36   351.1 1032.17   375.1  1031.9
   378.5 1032.31   388.7 1035.76   402.4 1042.56   412.7 1048.39   435.6 1063.26
#Mann= 4 ,-1,0
       0      .1       0  184.41    .045       0  206.02     .06       0
  405.96      .1       0
Bank Sta=184.41,206.02
XS Rating Curve= 0 ,0
Exp/Cntr(USF)=0,0
Exp/Cntr=0.3,0.1

Type RM Length L Ch R = 1 ,5687    ,297.7,299.6,302.1
XS GIS Cut Line= 6
1671568.09669226 508660.068607421671653.78451301508642.271398917
1671727.49991676  508628.45088851671825.78712176508610.021463424
1671899.50252551508596.1999687551671985.50399393508580.074672922
#Sta/Elev= 30
       0 1121.13     9.2 1117.68    22.6 1110.95      36 1105.17    62.8 1098.47
   102.9 1083.83   112.9 1080.67   126.3 1075.78   136.3  1070.5     143  1065.7
   146.3 1063.14     153 1056.25     173 1041.34   186.4 1033.75   196.4 1029.78
  204.041025.154   206.4 1024.26   213.1 1023.69   218.8 1024.07  223.391025.154
   239.8 1027.49   246.4 1027.96   346.6 1029.15   366.6 1030.59   376.6 1030.63
     380 1031.03   383.3 1032.55   403.3 1043.71     410 1048.19     425  1059.2
#Mann= 4 ,-1,0
       0      .1       0  204.04    .045       0  223.39     .06       0
  407.52      .1       0
Bank Sta=204.04,223.39
XS Rating Curve= 0 ,0
Exp/Cntr(USF)=0,0
Exp/Cntr=0.3,0.1

Type RM Length L Ch R = 1 ,5387    ,249.8,247.1,244.6
XS GIS Cut Line= 6
1671587.55014875508910.4893291721671674.98599749508913.896146519
1671749.92613633508916.8935158531671849.85474224508920.674020095
1671924.89199374508921.2491501851672012.45874774508921.143507345
#Sta/Elev= 30
       0  1115.9    22.3 1103.28    32.2 1099.85    68.3 1089.55    78.1 1085.44
    91.3  1077.5   101.1 1073.13   107.7 1068.53   124.1 1052.68     134 1044.45
   147.1 1036.43   160.2 1029.88  169.511022.559   173.4 1021.35   183.2 1021.03
   189.21022.556   196.3 1024.21   219.3 1023.39   242.3 1025.17   275.2 1024.25
   317.8  1026.1   334.2 1027.72   340.8 1027.75   347.3 1026.97   350.6 1027.49
   369.9 1041.05   383.4 1049.73   402.7 1065.28   412.9 1072.11   425.1 1079.16
#Mann= 5 ,-1,0
       0      .1       0   137.5     .06       0  169.51    .045       0
   189.2     .06       0  347.54      .1       0
Bank Sta=169.51,189.2
XS Rating Curve= 0 ,0
Exp/Cntr(USF)=0,0
Exp/Cntr=0.3,0.1

Type RM Length L Ch R = 1 ,5140    ,176.7,179.6,180.2
XS GIS Cut Line= 3
1671599.64175421509209.0211280731671948.17824452509124.983141831
1672079.98519136509072.791129323
#Sta/Elev= 30
       0 1119.92    10.5 1114.13    17.3 1111.31    40.9 1104.17    64.5 1090.15
    88.1 1080.14   101.6 1076.06   121.9 1071.79   128.6 1069.39   135.4 1064.52
   155.6 1044.29     186 1020.71  188.23 1019.57   190.2 1018.89   199.5 1018.59
   206.3 1019.57     213 1022.14   216.4 1022.44   250.1  1021.9   274.5 1023.34
   331.1 1024.95   347.9 1028.06   358.1 1028.45   368.7 1027.77   386.3 1037.03
   401.8 1042.38   414.6 1048.38   432.1 1060.47   460.4 1076.99   500.3 1093.11
#Mann= 3 ,-1,0
       0      .1       0  188.23    .045       0   206.3     .06       0
Bank Sta=188.23,206.3
XS Rating Curve= 0 ,0
Exp/Cntr(USF)=0,0
Exp/Cntr=0.3,0.1

Type RM Length L Ch R = 1 ,4961    ,176.1,179.1,178.8
XS GIS Cut Line= 3
  1671612.884465509359.4763145671671910.53969347509325.474348746
1672148.16391817509183.802516097
#Sta/Elev= 30
       0 1102.22     6.9 1101.12    13.5 1099.14      30 1091.81    36.6 1089.56
      63 1083.66    99.3 1073.05   112.5 1067.61     129 1059.52   135.7 1055.43
   142.3 1050.04   148.9 1045.55   162.1 1038.38   198.4 1021.79  212.111018.246
   218.2 1017.35   228.1 1017.11  236.811018.245   251.2    1020   316.2 1020.33
   400.3 1023.16   407.9 1023.74   417.1 1025.86   435.3 1025.86   438.4 1026.83
   446.1 1031.44   461.4 1036.29   495.1  1048.5   547.7 1070.89   576.2 1081.17
#Mann= 5 ,-1,0
       0      .1       0     210     .06       0  212.11    .045       0
  236.81     .06       0  499.59      .1       0
#XS Ineff= 2 , 0
                          320.14         1026.82
Permanent Ineff=
       F       F
Bank Sta=212.11,236.81
XS Rating Curve= 0 ,0
Exp/Cntr(USF)=0,0
Exp/Cntr=0.3,0.1

Type RM Length L Ch R = 1 ,4782    ,224.4,238.8,240.9
XS GIS Cut Line= 6
1671607.73539251509468.3616102491671702.03277609509491.796274677
1671785.77932775509503.9307648391671928.28274881509497.174447048
1671995.72368337509496.5381843071672105.40785637509624.647571224
#Sta/Elev= 30
       0  1080.6    23.7 1072.47    46.1 1066.72    55.9 1063.35    59.7 1061.41
    79.9 1047.99    96.9 1038.56   116.7 1029.77   136.6 1021.84   156.5 1018.82
  213.091016.625   232.3 1014.66   235.6 1014.94  239.411016.626   242.2 1017.86
   245.4 1018.28   294.7 1018.38     394 1021.68   403.9 1024.08     409  1024.5
   419.6 1024.61   433.6 1023.62   458.9 1023.23   468.5 1023.78   484.7 1028.17
   497.8 1033.98   519.4 1045.41   532.3 1054.78   549.6 1065.12   560.5  1070.5
#Mann= 6 ,-1,0
       0      .1       0  127.17     .05       0  213.09    .045       0
  239.41     .05       0  241.79     .06       0  481.89     .05       0
Bank Sta=213.09,239.41
XS Rating Curve= 0 ,0
Exp/Cntr(USF)=0,0
Exp/Cntr=0.3,0.1