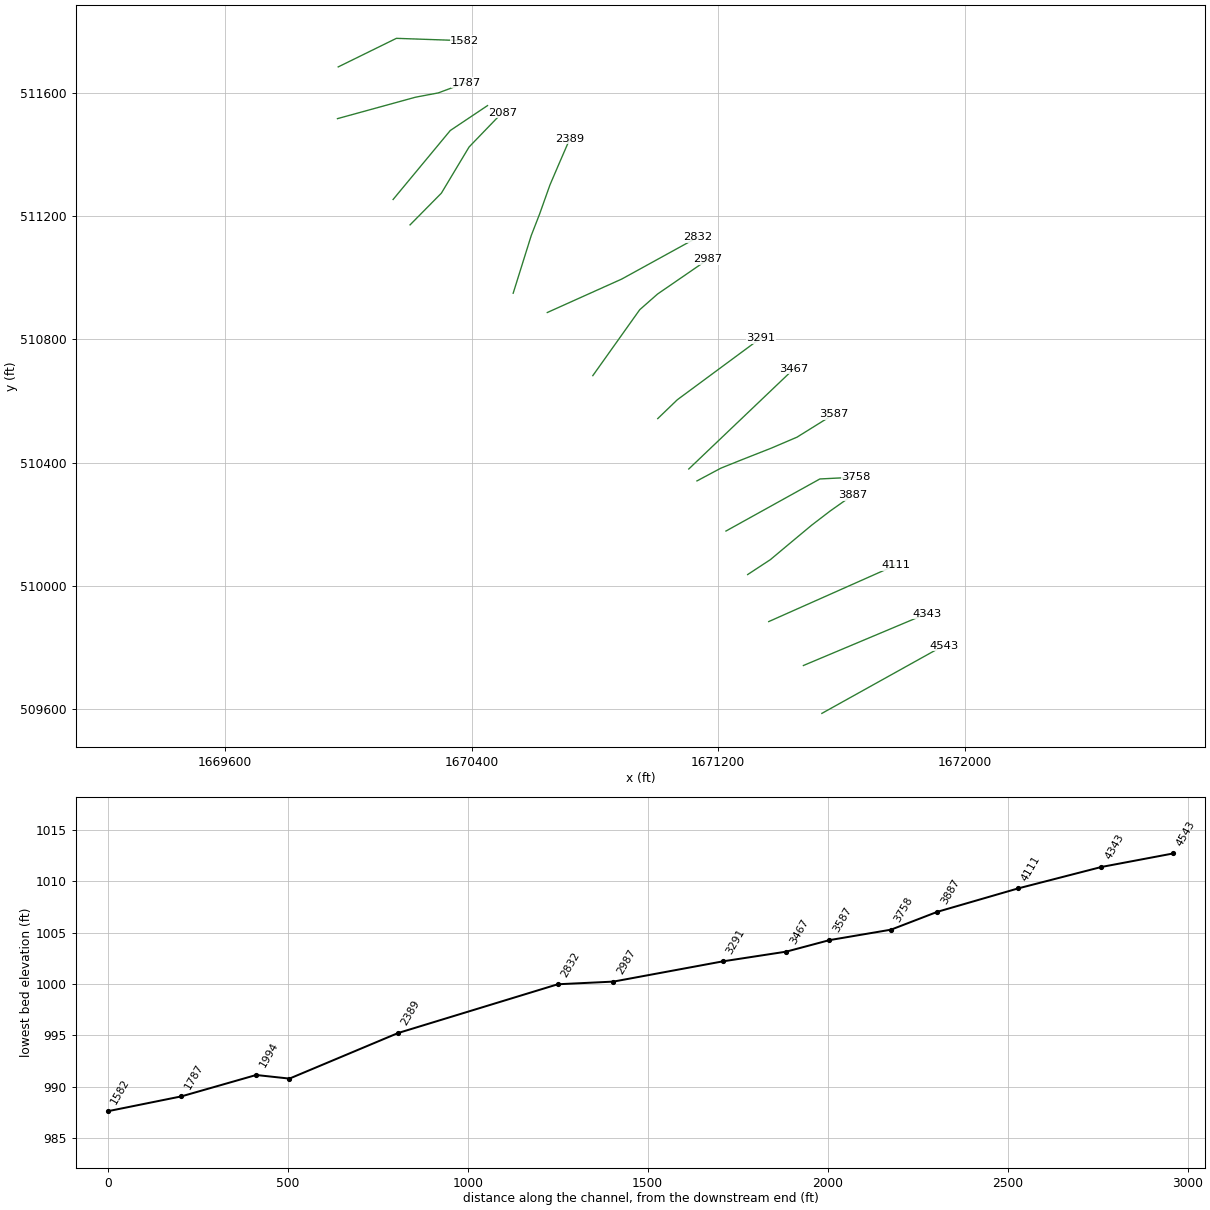
HEC-RAS study WilliamsRn.prj: WilliamsRn

--- WilliamsRn.g01 (geometry) --- (continued)

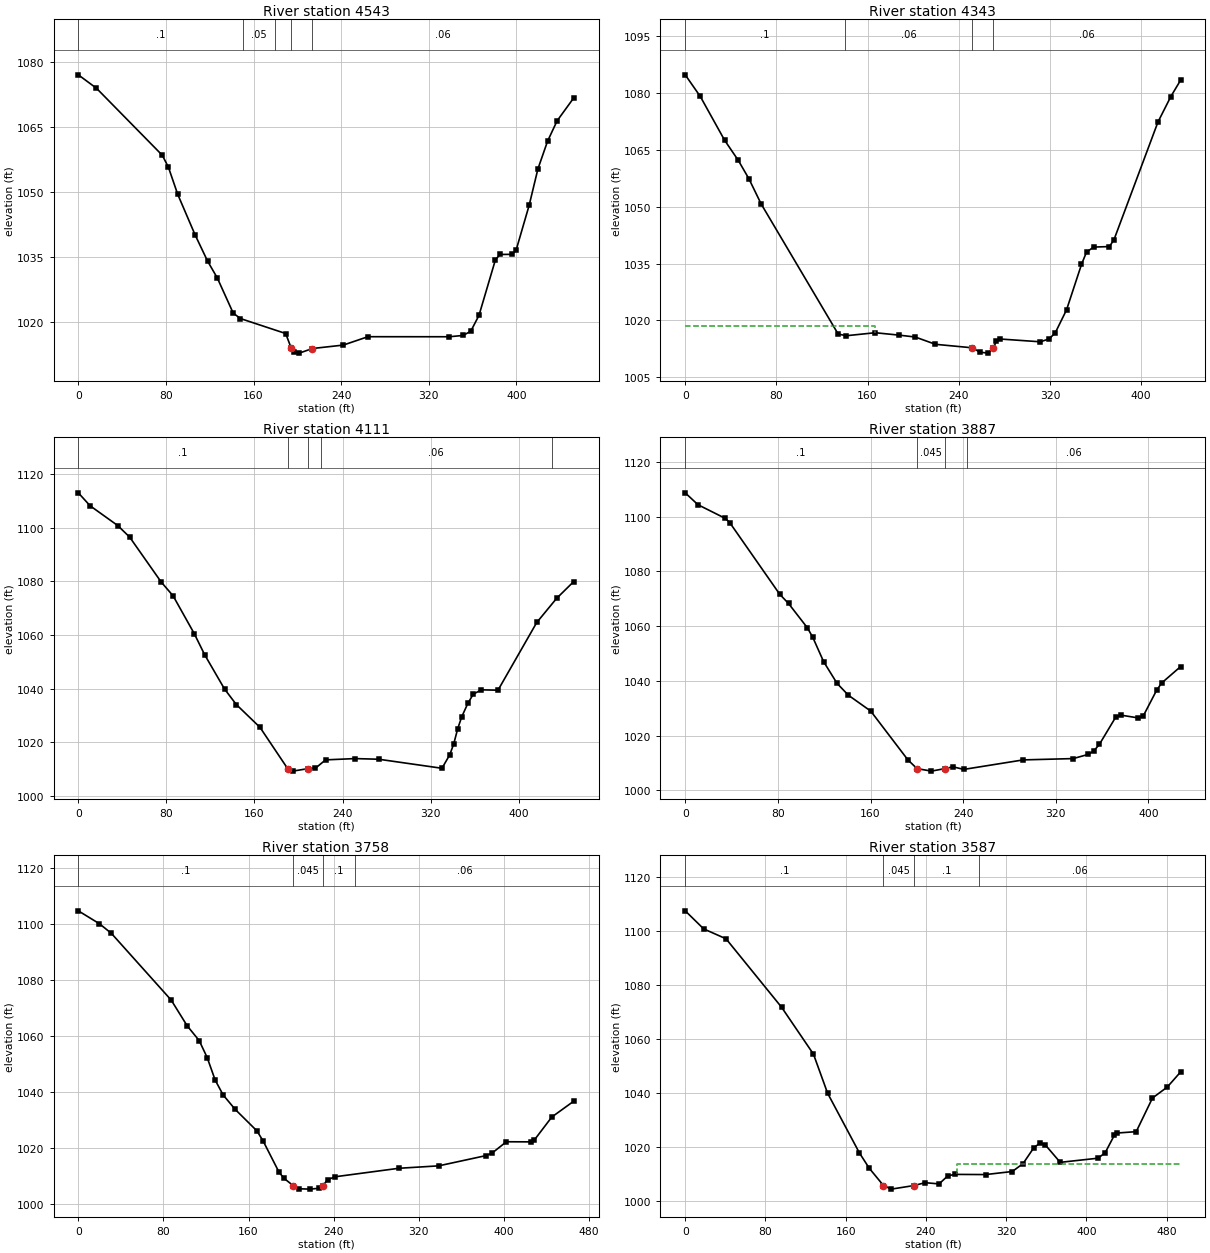
Type RM Length L Ch R = 1 ,4543    ,197.2,199.9,193
XS GIS Cut Line= 2
1671536.31058129509586.1729045031671931.50027217509806.125314052
#Sta/Elev= 30
       0 1077.13    16.6 1074.02    76.7 1058.51    82.3 1055.72    90.7 1049.51
   106.7 1040.05     118 1034.03   126.9 1030.12   141.4    1022     148 1020.73
   189.3 1017.27   194.5 1013.81   196.8    1013   201.7 1012.73   213.8  1013.8
   241.9 1014.59   264.4 1016.53   338.6 1016.52   351.3 1016.82   358.3  1017.8
   365.8 1021.47   380.8 1034.33     385 1035.56   395.8 1035.59   399.6 1036.48
   411.6 1046.94   419.6 1055.36   428.4 1061.77   437.1 1066.48   452.3 1071.79
#Mann= 5 ,-1,0
       0      .1       0     150     .05       0     180     .06       0
   194.5    .045       0   213.8     .06       0
Bank Sta=194.5,213.8
XS Rating Curve= 0 ,0
Exp/Cntr(USF)=0,0
Exp/Cntr=0.3,0.1

Type RM Length L Ch R = 1 ,4343    ,228.9,231.6,229.4
XS GIS Cut Line= 2
1671476.32680774509741.5330707641671877.00056689509910.078455595
#Sta/Elev= 30
       0 1084.67    13.2 1078.99    34.5 1067.48    46.5 1062.18    55.9  1057.3
    66.6 1050.69   134.2 1016.43   141.3 1015.99   166.7 1016.78   187.6 1016.15
   201.8 1015.65   219.6 1013.73   251.71012.817   258.8 1011.65   265.9 1011.41
  270.47 1012.82     273 1014.56   276.6 1015.12   311.7 1014.39   319.3 1015.17
   324.6 1016.71   334.6 1022.81   347.7 1034.76   352.1 1038.01   358.4 1039.33
   372.2 1039.46   376.2 1041.26   414.8 1072.25   426.1 1078.96   434.7 1083.28
#Mann= 4 ,-1,0
       0      .1       0     140     .06       0   251.7    .045       0
  270.47     .06       0
#XS Ineff= 2 , 0
          166.19 1018.53
Permanent Ineff=
       F       F
Bank Sta=251.7,270.47
XS Rating Curve= 0 ,0
Exp/Cntr(USF)=0,0
Exp/Cntr=0.3,0.1

Type RM Length L Ch R = 1 ,4111    ,219.3,224.3,226.5
XS GIS Cut Line= 2
1671363.87855896509884.0889195531671775.06730237510066.942160359
#Sta/Elev= 30
       0 1112.94    10.7 1108.12    35.8 1100.76    46.6 1096.47    75.3 1079.72
    86.1 1074.58   105.3 1060.52   114.8 1052.63   132.8  1039.9   143.5 1034.12
     165 1025.63   190.2 1010.22   194.8 1009.32   208.2 1010.22   215.4 1010.42
   224.6 1013.51   251.3 1013.99   272.8 1013.75   330.3 1010.38   337.4 1015.41
     341 1019.47   344.6  1025.1   348.2 1029.47   353.8 1034.54   358.8 1038.01
   366.2 1039.59   381.2 1039.45   416.4 1064.66   434.4 1073.62     450 1079.91
#Mann= 5 ,-1,0
       0      .1       0   190.2    .045       0   208.2      .1       0
     220     .06       0     430      .1       0
Bank Sta=190.2,208.2
XS Rating Curve= 0 ,0
Exp/Cntr(USF)=0,0
Exp/Cntr=0.3,0.1

Type RM Length L Ch R = 1 ,3887    ,131.2,128.9,127.3
XS GIS Cut Line= 6
1671295.58378585510036.7961689231671369.32937326510085.208473668
1671426.80629243510133.3894796671671503.62864535 510197.40805243
1671563.52747567510243.2918189171671636.37608325510294.633579761
#Sta/Elev= 30
       0 1108.65      11 1104.31    34.5 1099.34    38.4  1097.8    81.6 1071.62
    89.2 1068.25   105.5 1059.36   110.1 1055.94   119.5 1047.02   131.1 1039.09
   140.9 1034.75   160.2 1028.96   192.2 1011.19   200.1 1007.97   212.6 1007.04
  224.09 1007.95   231.2 1008.61   240.6 1007.67   291.9 1011.14     335 1011.62
   348.2 1013.17   352.9 1014.45   357.6 1016.79   371.7 1026.73   376.4 1027.47
   391.3 1026.46   395.4 1027.08     407 1036.52   411.4 1039.21   427.8 1045.22
#Mann= 4 ,-1,0
       0      .1       0   200.1    .045       0  224.09      .1       0
  243.22     .06       0
Bank Sta=200.1,224.09
XS Rating Curve= 0 ,0
Exp/Cntr(USF)=0,0
Exp/Cntr=0.3,0.1

Type RM Length L Ch R = 1 ,3758    ,173.1,171.1,169
XS GIS Cut Line= 3
1671225.11865226510177.9913547771671529.81778366510347.050227683
 1671646.7829341510352.947630226
#Sta/Elev= 30
       0 1104.65    19.8 1100.05      31 1096.64    87.3 1072.78   102.3 1063.61
   113.6 1058.33   121.1 1052.28   128.6 1044.25   136.1 1038.92   147.4 1033.78
   167.8 1026.11   173.6 1022.55   188.6 1011.37   193.2 1009.19  201.781006.594
   207.4 1005.43   217.4  1005.3   226.1 1005.59  229.911006.595   234.3 1008.64
   241.1  1009.7   301.2 1012.74   338.7 1013.61   383.5  1017.3   389.2 1018.27
   402.3 1022.21   425.3 1022.17   428.6 1022.85     445 1031.04   465.6 1036.69
#Mann= 4 ,-1,0
       0      .1       0  201.78    .045       0  229.91      .1       0
     260     .06       0
Bank Sta=201.78,229.91
XS Rating Curve= 0 ,0
Exp/Cntr(USF)=0,0
Exp/Cntr=0.3,0.1

Type RM Length L Ch R = 1 ,3587    ,113.5,119.8,124.7
XS GIS Cut Line= 6
1671131.06967917510340.666296095 1671208.6613875510382.101252586
1671278.26000158510410.0526402591671371.30082601510446.704797924
1671455.58061062510482.6778532261671574.01953806510556.394429176
#Sta/Elev= 30
       0 1107.57    18.4 1100.87    40.7 1097.19    96.1 1071.79   127.9 1054.38
     142 1039.88   173.8 1017.67   183.6    1012  197.731005.619   205.5 1004.28
  228.28 1005.62   239.2 1006.67   253.2 1006.22     262 1009.25   269.1 1009.75
   299.5 1009.68   326.2 1010.82   336.9 1013.74   347.6 1019.61   354.1 1021.47
   359.3 1020.62     374 1014.22   411.7 1015.76   418.8 1017.77   428.1 1024.37
   430.7  1025.1   449.8 1025.61     466 1038.09   480.8 1042.17   494.1 1047.78
#Mann= 4 ,-1,0
       0      .1       0  197.73    .045       0  228.28      .1       0
  292.96     .06       0
#XS Ineff= 2 , 0
                          270.76         1013.74
Permanent Ineff=
       F       F
Bank Sta=197.73,228.28
XS Rating Curve= 0 ,0
Exp/Cntr(USF)=0,0
Exp/Cntr=0.3,0.1

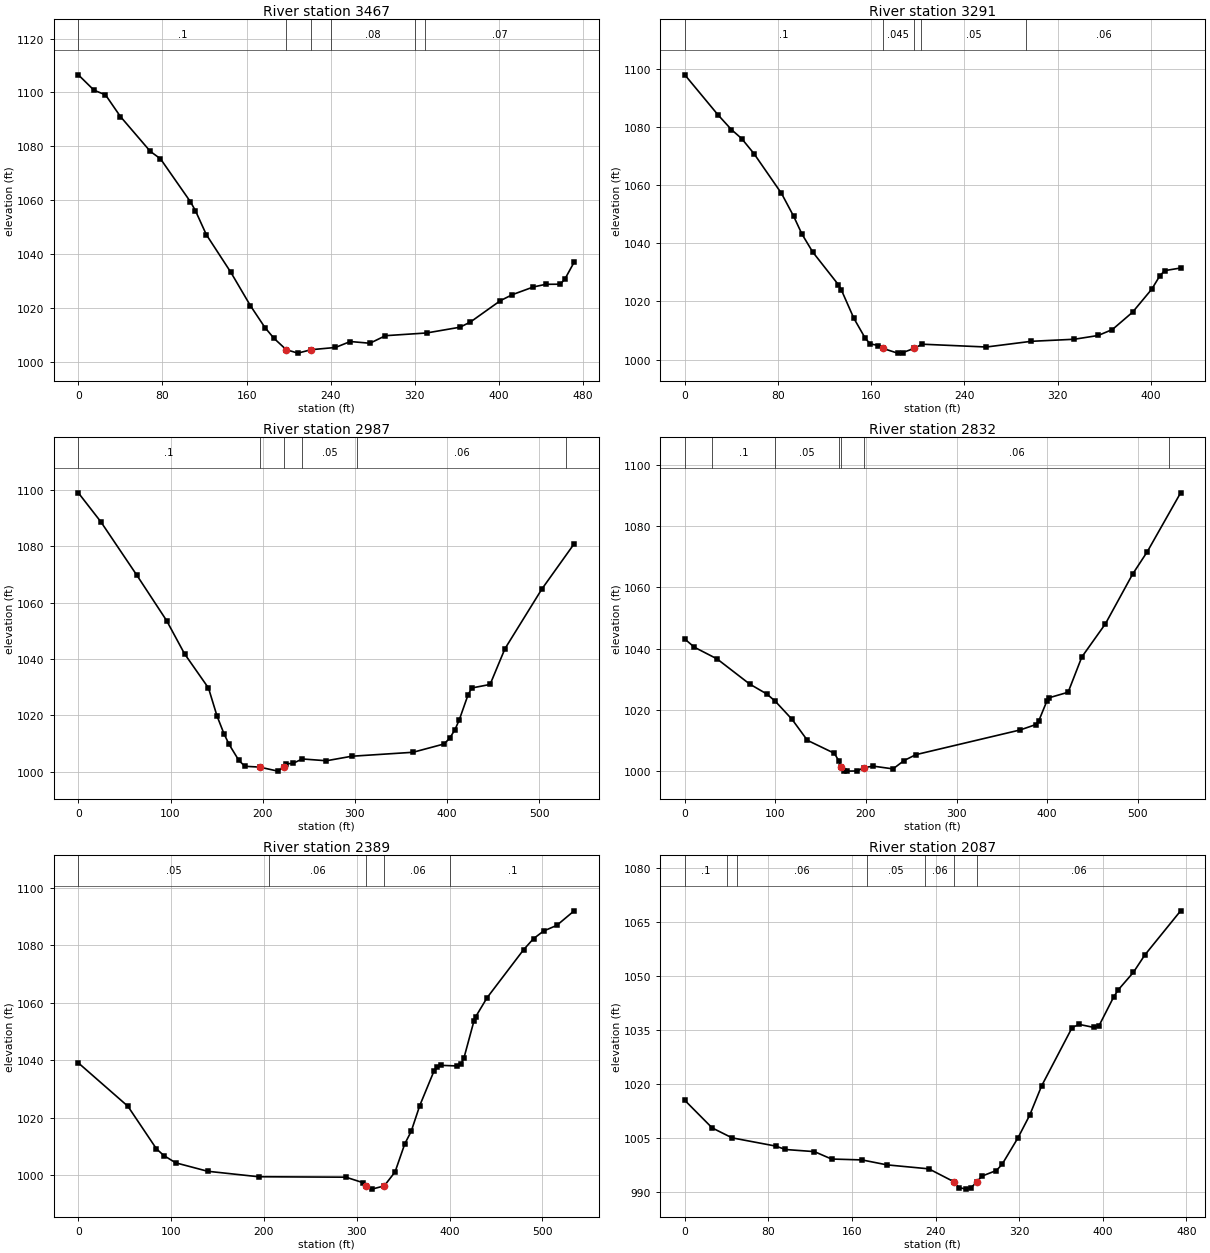
Type RM Length L Ch R = 1 ,3467    ,178.5,176.7,175.4
XS GIS Cut Line= 2
1671104.51638455510379.3830443371671445.58283164510704.723084643
#Sta/Elev= 30
       0 1106.55      15  1100.8    25.8 1099.13      40 1091.06    68.4 1078.12
    78.1 1075.35   106.6 1059.38   111.3 1056.11   121.7 1047.17   144.9 1033.24
   163.6 1020.79   177.4 1012.68     186 1008.67  197.65 1004.44   208.7 1003.16
   221.5 1004.44   244.4 1005.26   258.6 1007.47   277.2 1006.83     292 1009.64
   331.1 1010.65   362.9 1012.79   372.8 1014.73   401.3 1022.66   412.7 1024.89
   432.7 1027.75   444.5 1028.73   458.2 1028.76   462.6 1030.68   471.4 1036.96
#Mann= 6 ,-1,0
       0      .1       0  197.65    .045       0   221.5      .1       0
     240     .08       0     320     .06       0     330     .07       0
Bank Sta=197.65,221.5
XS Rating Curve= 0 ,0
Exp/Cntr(USF)=0,0
Exp/Cntr=0.3,0.1

Type RM Length L Ch R = 1 ,3291    ,297.8,303.6,306.6
XS GIS Cut Line= 6
1671003.87849844510543.0172157071671067.35606178510604.126673542
1671127.66893328510648.7066368831671208.08609528510708.146150537
1671268.39896678510752.726113878 1671338.7643116510804.735524289
#Sta/Elev= 30
       0 1097.83    28.4 1084.12      40 1079.02    48.8 1075.93    59.4 1070.74
      83 1057.09    93.5 1049.19   100.5 1043.15   109.8 1036.95   131.8 1025.74
   134.5 1023.82   145.1 1014.19   154.9 1007.32   159.1 1005.39   166.2 1004.83
   169.81003.871   182.6 1002.21   187.3 1002.41  196.941003.872   203.7 1005.28
   258.8 1004.31   297.4 1006.27   334.4 1006.98   354.8 1008.27     367 1010.31
   384.3 1016.25   400.8 1024.18   407.8 1028.79   411.9 1030.55   425.6 1031.46
#Mann= 5 ,-1,0
       0      .1       0   169.8    .045       0  196.94      .1       0
  203.11     .05       0  293.11     .06       0
Bank Sta=169.8,196.94
XS Rating Curve= 0 ,0
Exp/Cntr(USF)=0,0
Exp/Cntr=0.3,0.1

Type RM Length L Ch R = 1 ,2987    ,160.2,154.6,146.8
XS GIS Cut Line= 6
1670793.25342567510682.3982241751670843.96296993510753.705824345
1670887.42712183510814.8277493421670945.37943375510896.323649332
1671002.94263884510947.0305689281671166.66153271511059.688348535
#Sta/Elev= 30
       0    1099    24.4 1088.73    63.5 1069.75    95.7 1053.69   115.2 1041.89
   141.2 1029.73   150.5 1019.76     158 1013.52   163.6  1009.7     174 1004.12
   180.6 1001.96  196.651001.677   216.4 1000.24  222.641001.676   225.8 1002.84
   232.9 1002.99   242.9 1004.56   269.2 1003.92   296.5 1005.52   363.1 1006.93
   396.8 1009.88   402.9 1011.94   408.6 1014.96   413.3 1018.47   422.7 1027.24
   426.8 1029.74   446.7    1031   462.8 1043.67   502.9 1064.87   537.9 1080.91
#Mann= 6 ,-1,0
       0      .1       0  196.65    .045       0  222.64      .1       0
   242.5     .05       0   302.5     .06       0  529.21      .1       0
Bank Sta=196.65,222.64
XS Rating Curve= 0 ,0
Exp/Cntr(USF)=0,0
Exp/Cntr=0.3,0.1

Type RM Length L Ch R = 1 ,2832    ,431.3,443.6,446.9
XS GIS Cut Line= 3
1670645.61928043510887.2854750711670887.17456391510995.958935162
1671134.66003371 511132.16607399
#Sta/Elev= 30
       0 1043.12    10.5 1040.45    35.6 1036.63    71.6 1028.42    90.6 1025.16
     100 1022.77   118.4 1016.89   135.3 1010.05   165.1  1005.8     170 1003.36
   172.8 1001.32   175.9 1000.04   179.5  999.98   190.3 1000.03   198.1 1001.15
   208.3  1001.6   229.9 1000.71     242 1003.42   255.1 1005.36   370.3 1013.43
   387.5 1015.18   390.7 1016.33   399.6 1022.76     402 1023.92   423.2 1025.74
   438.3 1037.24   464.4  1048.1   494.4 1064.31   510.7 1071.69   547.4 1090.86
#Mann= 7 ,-1,0
       0     .05       0      30      .1       0     100     .05       0
     170     .06       0   172.8    .045       0   198.1     .06       0
  534.88      .1       0
Bank Sta=172.8,198.1
XS Rating Curve= 0 ,0
Exp/Cntr(USF)=0,0
Exp/Cntr=0.3,0.1

Type RM Length L Ch R = 1 ,2389    ,303.8,301.8,299.6
XS GIS Cut Line= 6
1670534.92823561510949.9297507931670593.39752617 511136.79560934
1670620.58480775511206.8007186651670654.09327093511301.086947426
1670683.74642684 511370.37355426 1670718.6978005511451.079101503
#Sta/Elev= 30
       0 1039.08    53.4 1024.02    84.2 1009.22    92.1 1006.91   104.9 1004.37
   139.3 1001.44   194.3  999.53   288.3  999.38   306.3  997.52  310.01 996.357
   316.5  995.23  329.65996.3571   341.3  1001.2   351.8 1010.98   358.7  1015.3
   367.9 1024.24   383.4 1036.36     387  1037.8   390.3 1038.24     408 1038.02
     412 1038.54   415.5 1040.75   426.2 1053.51   428.1 1055.07   440.5 1061.74
   479.8  1078.4   490.5 1082.24   501.3 1084.88   515.6 1086.86   534.3 1091.91
#Mann= 5 ,-1,0
       0     .05       0   205.8     .06       0  310.01    .045       0
  329.65     .06       0  400.96      .1       0
Bank Sta=310.01,329.65
XS Rating Curve= 0 ,0
Exp/Cntr(USF)=0,0
Exp/Cntr=0.3,0.1

Type RM Length L Ch R = 1 ,2087    ,95.2,92.5,90.5
XS GIS Cut Line= 5
1670200.43360355511171.7763852451670301.97816151511274.672302082
1670340.56666701511338.9835251721670392.01603918511424.733025596
1670499.50796381511536.209055317
#Sta/Elev= 30
       0 1015.48    26.2 1007.81    45.2 1005.05      87 1002.76    96.3 1001.81
     124 1001.22   140.4  999.16   169.6  998.91   193.3  997.54   233.5  996.43
  257.52992.8373   262.2  991.24   269.1  990.79   274.1  991.21  279.32992.8354
   284.4  994.42   298.1  995.97   303.5  997.64   318.8 1005.06     330 1011.35
   341.4  1019.5   370.6 1035.72   377.3  1036.6   391.5 1035.75   396.2 1036.16
   410.3  1044.2   414.7  1046.2   429.2 1051.07   440.2 1055.92   474.4 1068.18
#Mann= 7 ,-1,0
       0      .1       0      40     .05       0      50     .06       0
  174.56     .05       0  229.56     .06       0  257.52    .045       0
  279.32     .06       0
Bank Sta=257.52,279.32
XS Rating Curve= 0 ,0
Exp/Cntr(USF)=0,0
Exp/Cntr=0.3,0.1

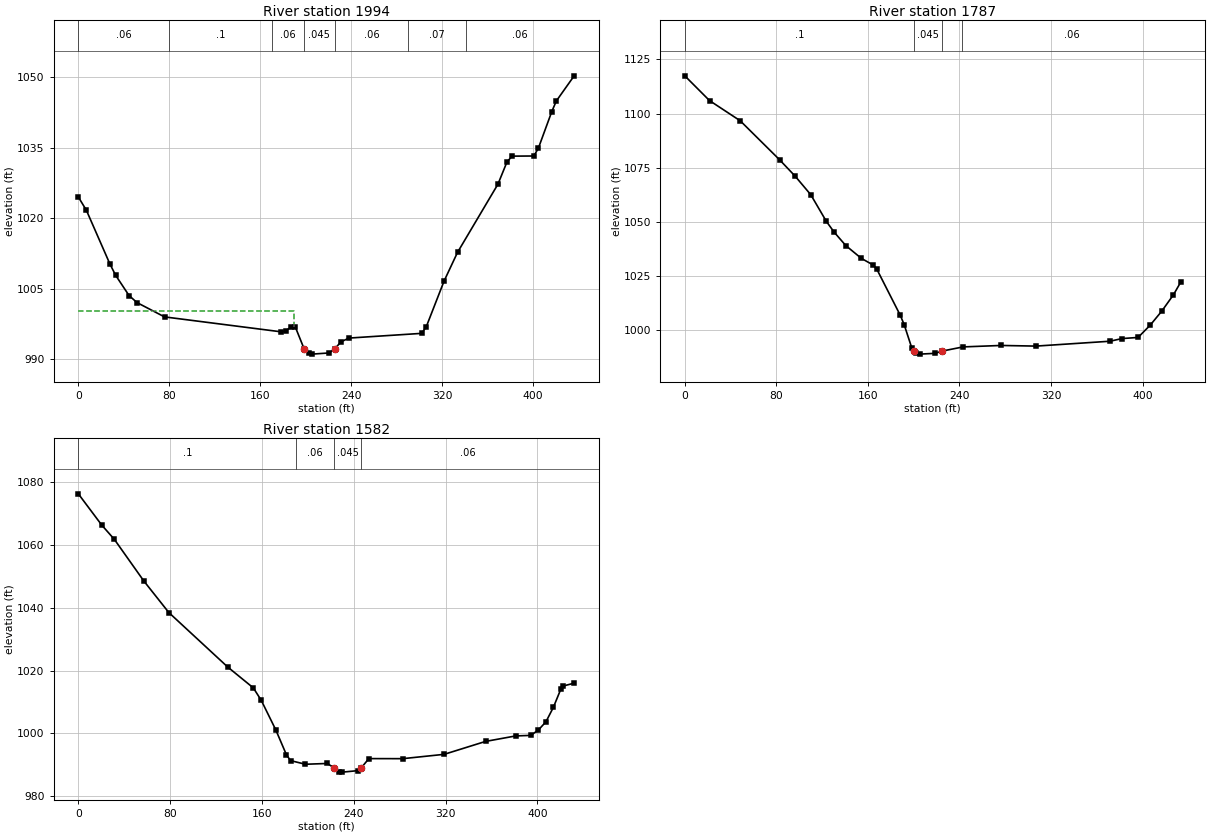
Type RM Length L Ch R = 1 ,1994    ,214.8,207.5,200.2
XS GIS Cut Line= 3
1670145.39723919511254.1806558291670330.85853595511478.040595811
1670451.66027438511558.922379579
#Sta/Elev= 30
       0 1024.52     7.1 1021.69    27.6 1010.38    32.8 1007.89    44.6 1003.59
    51.6 1002.09    75.8  999.05     178  995.89   182.3  996.01   187.1  996.94
   190.8  996.93  198.56992.2806   202.5  991.32   205.4  991.14   220.6  991.39
  225.55992.2807     231  993.74     238  994.55   301.9  995.55   305.9  996.88
   321.7 1006.67   333.5 1012.75   369.1 1027.26     377 1031.96   381.5  1033.2
   400.6 1033.23   404.6 1034.87   416.4 1042.65   420.4 1044.91   436.1 1050.26
#Mann= 7 ,-1,0
       0     .06       0      80      .1       0     170     .06       0
  198.56    .045       0  225.55     .06       0     290     .07       0
   340.7     .06       0
#XS Ineff= 2 , 0
          189.53 1000.27
Permanent Ineff=
       F       F
Bank Sta=198.56,225.55
XS Rating Curve= 0 ,0
Exp/Cntr(USF)=0,0
Exp/Cntr=0.3,0.1

Type RM Length L Ch R = 1 ,1787    ,208.3,204.8,200.9
XS GIS Cut Line= 6
1669965.04510833511516.5963589251670049.41337793 511539.79644376
 1670121.7288501511559.682558835  1670218.149589511586.197925761
1670292.10088468511600.1358900071670381.58003642 511633.56987825
#Sta/Elev= 30
       0 1117.42    21.6    1106    48.4  1096.7    82.8 1078.72    96.5  1071.1
   110.1 1062.58   123.7 1050.29   130.5 1045.33   140.7 1039.13   154.3 1033.22
   164.5  1030.2   167.9 1028.14   188.3 1006.97   191.7 1002.68   198.5  991.67
   200.4 990.454   201.9  989.45   205.3  989.06   218.9  989.43  224.74990.4529
   243.2  992.39   276.5  993.06   306.8  992.76   371.6  995.01   382.1  996.24
   396.1  996.75   406.7 1002.41   416.8 1008.88     427 1016.41   433.3 1022.18
#Mann= 4 ,-1,0
       0      .1       0   200.4    .045       0  224.74      .1       0
   242.5     .06       0
Bank Sta=200.4,224.74
XS Rating Curve= 0 ,0
Exp/Cntr(USF)=0,0
Exp/Cntr=0.3,0.1

Type RM Length L Ch R = 1 ,1582    ,217.1,228.9,237.7
XS GIS Cut Line= 3
1669967.52115693511684.5425248861670156.14525533511777.250774398
1670377.91500933511769.508154464
#Sta/Elev= 30
       0 1076.31    20.4 1066.35    31.4 1061.79      57 1048.57    78.9 1038.46
   130.1 1021.14   152.5 1014.46   159.4  1010.5   172.1 1001.06   181.3  993.18
   184.9  991.29   197.9  990.12   217.1  990.37  222.39989.0579   226.9  987.69
   230.2  987.61   243.3  988.07  246.71989.0564   253.2  991.92   282.7   991.9
   318.8  993.28   354.9   997.4   381.2  999.15   394.3  999.32   400.9 1001.03
   407.5 1003.65     414 1008.27   420.6 1014.17   422.6 1015.06   432.1 1015.97
#Mann= 4 ,-1,0
       0      .1       0     190     .06       0  222.39    .045       0
  246.71     .06       0
Bank Sta=222.39,246.71
XS Rating Curve= 0 ,0
Exp/Cntr(USF)=0,0
Exp/Cntr=0.3,0.1