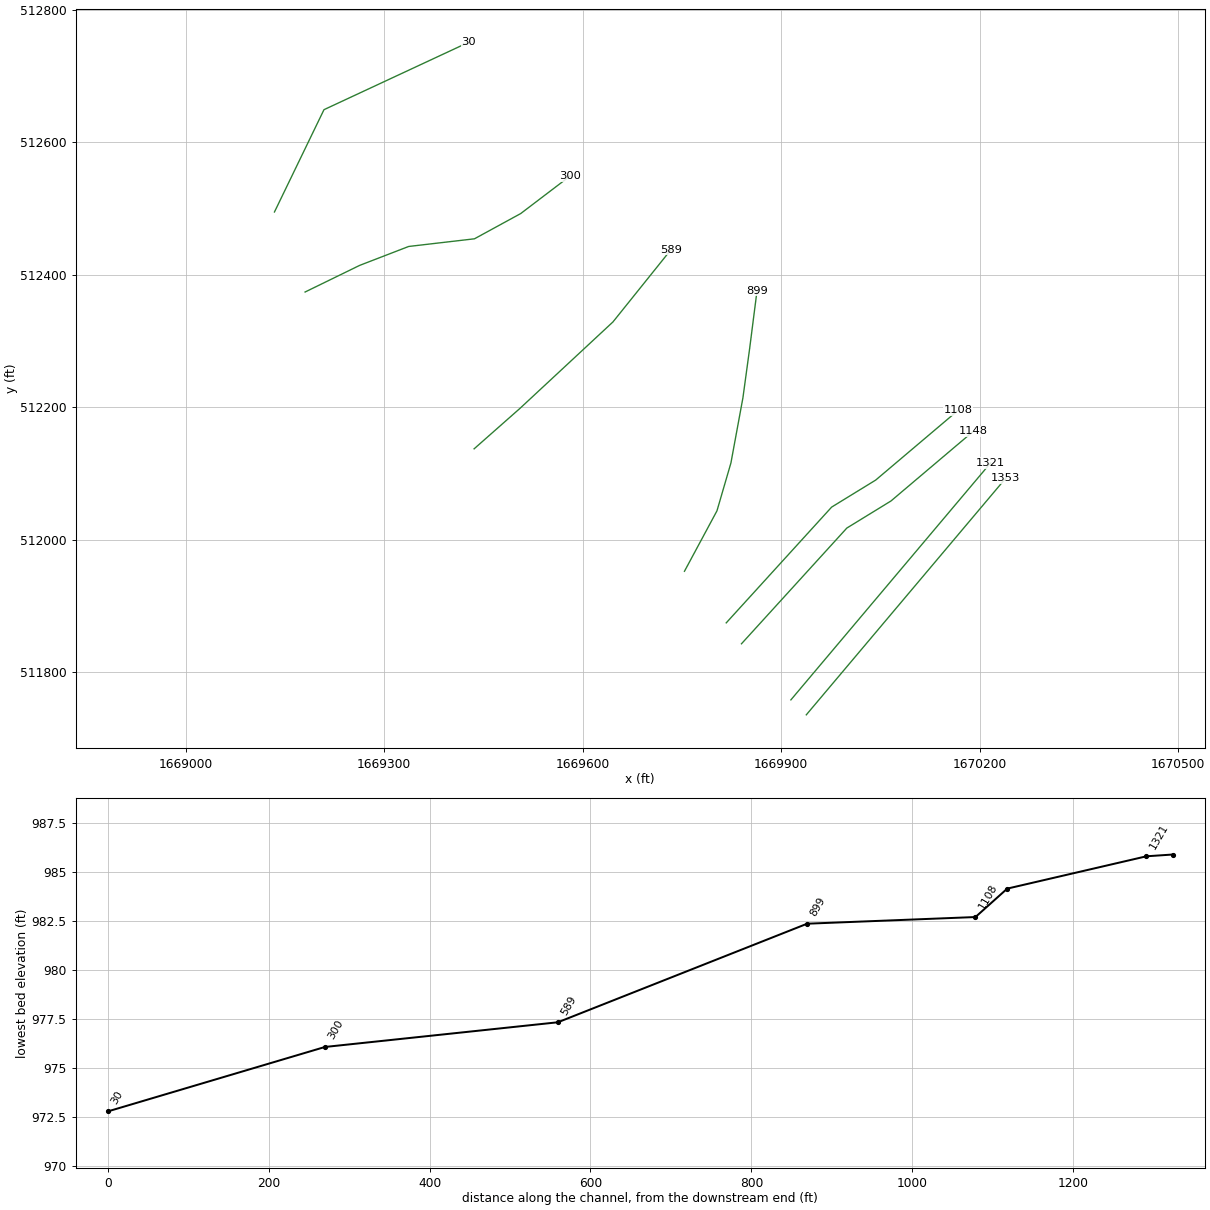
HEC-RAS study WilliamsRn.prj: WilliamsRn

--- WilliamsRn.g01 (geometry) --- (continued)

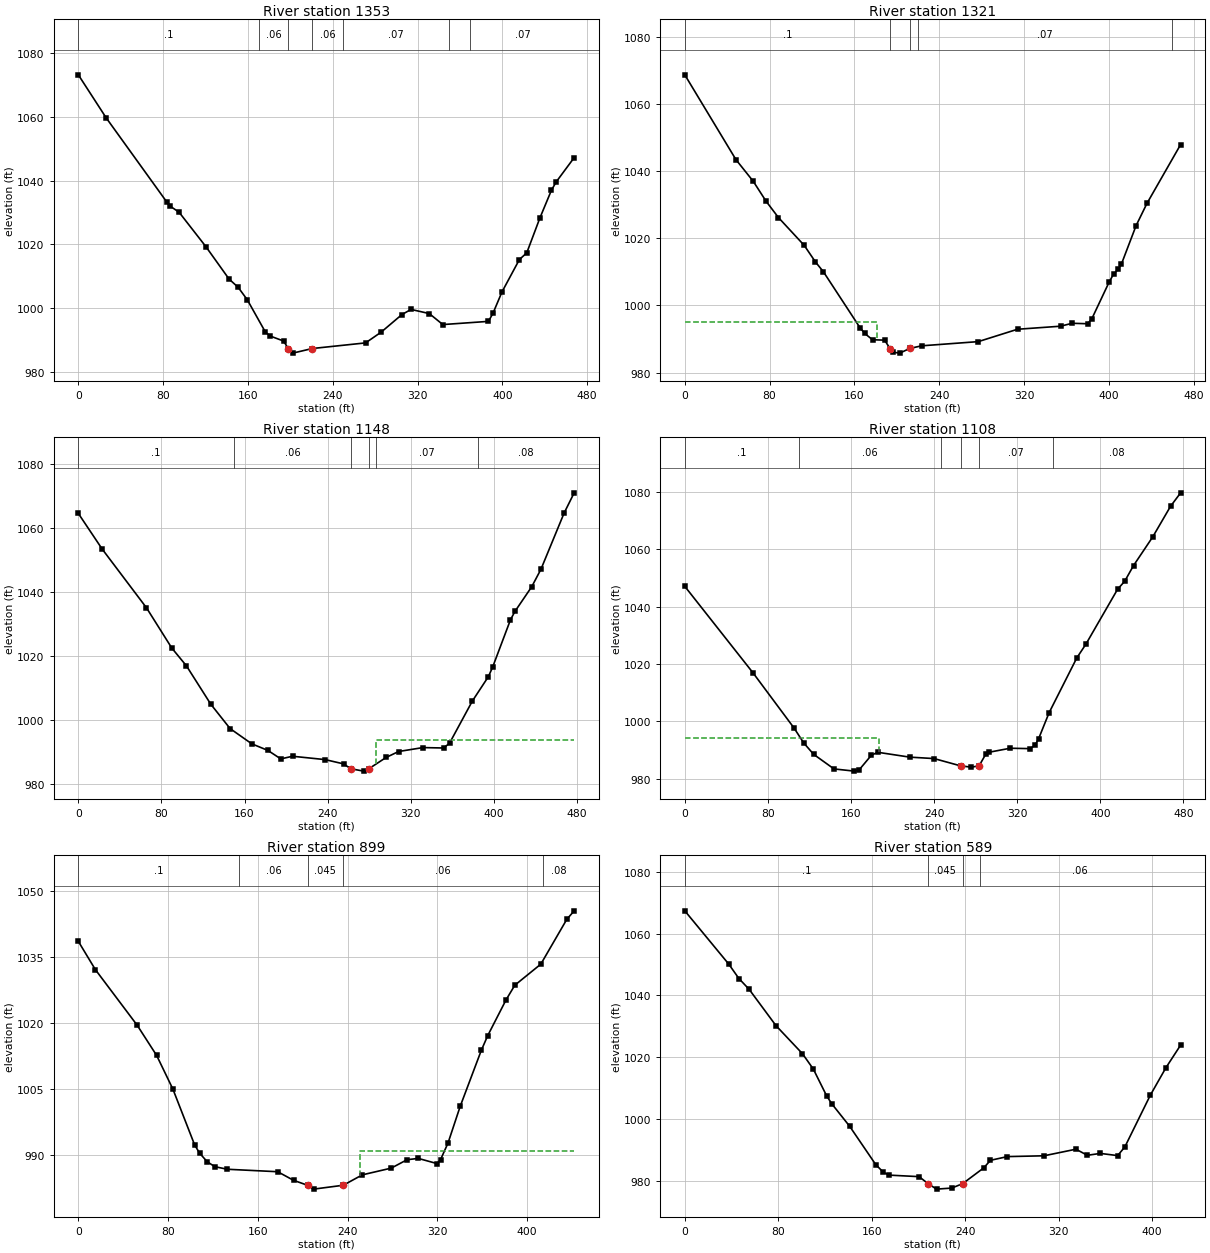
Type RM Length L Ch R = 1 ,1353    ,32.5,32.6,33
XS GIS Cut Line= 2
1669937.96052779511735.3335114721670239.62151397512092.884181562
#Sta/Elev= 30
       0 1073.18    26.3 1059.67    83.2  1033.4    86.4 1032.03      95  1030.1
   120.4 1019.26   142.2 1009.12   150.8 1006.52   159.4 1002.62   176.5  992.48
   181.1  991.23   193.7  989.67     198  987.33   202.3  985.88  220.72987.3235
     271  989.09   285.7  992.46   305.3  997.98   313.9  999.59   331.1  998.29
   343.9  994.84   386.9  995.84   391.2  998.37   399.7 1005.08   416.1 1015.22
   423.1 1017.35   435.5  1028.3   446.4 1037.01     451 1039.66   467.8  1047.2
#Mann= 7 ,-1,0
       0      .1       0     170     .06       0     198    .045       0
  220.72     .06       0     250     .07       0     350     .06       0
     370     .07       0
Bank Sta=198,220.72
XS Rating Curve= 0 ,0
Exp/Cntr(USF)=0,0
Exp/Cntr=0.3,0.1

Type RM Length L Ch R = 1 ,1321    ,171,173,163.5
XS GIS Cut Line= 2
1669914.67315949511757.9043453551670216.33414568512115.455015445
#Sta/Elev= 30
       0 1068.78    48.3 1043.47    64.6 1037.02    76.7 1031.08    88.4  1026.2
   112.7 1017.91   123.3 1012.97   130.8 1010.04   165.2  993.42   169.8  991.65
   177.1  989.78   188.5  989.66  193.63  987.17   196.9  986.05   202.8  985.79
   212.2  987.18   223.4  987.97   276.9  989.22   313.9  992.91   354.6  993.82
   365.4  994.69   380.1  994.55     384  996.02   400.4 1007.01   404.6 1009.39
   408.8 1010.76     412 1012.39   425.8 1023.82     436 1030.42   467.8 1047.99
#Mann= 5 ,-1,0
       0      .1       0  193.63    .045       0   212.2     .06       0
     220     .07       0     460      .1       0
#XS Ineff= 2 , 0
          180.87  994.94
Permanent Ineff=
       F       F
Bank Sta=193.63,212.2
XS Rating Curve= 0 ,0
Exp/Cntr(USF)=0,0
Exp/Cntr=0.3,0.1

Type RM Length L Ch R = 1 ,1148    ,39.3,39.5,39.2
XS GIS Cut Line= 4
1669839.97321149511842.5454623261669999.22421976512017.289801413
1670065.86191979512058.1322627251670190.14273113512163.200418306
#Sta/Elev= 30
       0 1064.69      23 1053.53    65.6 1035.19      90  1022.6   104.1 1017.03
   127.5 1005.06   146.1  997.44     167  992.67   182.5  990.61   194.9  987.96
   206.2  988.79   237.6  987.74   255.4   986.4  262.17  984.89   274.6  984.14
   279.6  984.87   296.3  988.42   308.3  990.27   331.7   991.5   351.6  991.37
   357.3  992.85   379.3 1006.05   394.7 1013.66   398.9 1016.71     416 1031.45
   420.3 1034.06   436.5  1041.8   445.4 1047.29   467.6 1064.79   477.3 1071.13
#Mann= 6 ,-1,0
       0      .1       0     150     .06       0  262.17    .045       0
   279.6     .06       0  286.42     .07       0  384.58     .08       0
#XS Ineff= 2 , 0
                          286.28          993.97
Permanent Ineff=
       F       F
Bank Sta=262.17,279.6
XS Rating Curve= 0 ,0
Exp/Cntr(USF)=0,0
Exp/Cntr=0.3,0.1

Type RM Length L Ch R = 1 ,1108    ,193.5,209.2,214
XS GIS Cut Line= 4
1669816.97411585511874.1591492381669976.22512411512048.903488325
1670042.86282415512089.7459496381670167.14363548512194.814105219
#Sta/Elev= 30
       0 1047.03    65.7  1016.9   105.2  997.68   114.6  992.45   124.1  988.52
   143.6  983.46   163.2  982.69   167.9  983.16   179.5  988.18   185.6  989.26
   216.6  987.56     240  987.06  265.54  984.52   275.8  984.07  283.28  984.52
     290  988.77   292.5  989.24   313.2  990.66   332.6  990.52   337.2  991.75
   340.5  993.89   350.7 1003.04   377.4 1022.15   386.1 1026.89   416.7 1046.07
   423.4 1048.77     432 1054.29   450.5 1064.28   467.6 1074.91   477.3  1079.6
#Mann= 6 ,-1,0
       0      .1       0     110     .06       0  246.42     .07       0
  265.54    .045       0  283.28     .07       0  354.58     .08       0
#XS Ineff= 2 , 0
          187.36  994.25
Permanent Ineff=
       F       F
Bank Sta=265.54,283.28
XS Rating Curve= 0 ,0
Exp/Cntr(USF)=0,0
Exp/Cntr=0.3,0.1

Type RM Length L Ch R = 1 ,899     ,319.9,309.8,301.4
XS GIS Cut Line= 6
1669753.84900843511952.0213410851669802.96242726512043.274767503
1669824.04178143512115.4747543341669842.17429109 512213.83774659
1669852.35077992512288.3697497551669863.48888101512375.499496758
#Sta/Elev= 30
       0 1038.59    15.2 1032.17    52.5 1019.53    69.8 1012.69    84.3 1005.04
   103.6  992.42     108  990.54   114.8  988.58   121.6  987.45   132.8  986.86
   177.7   986.3   191.8  984.35  204.26983.2296   209.7  982.35  236.09 983.229
   253.1  985.59   278.9  987.12     293  989.03     303  989.32   319.5  988.16
   322.8  989.03   329.5  992.83   340.3 1001.12   359.2 1013.89   364.9 1017.21
   381.2 1025.31     389 1028.63   412.2 1033.42   435.3 1043.57   441.9 1045.52
#Mann= 5 ,-1,0
       0      .1       0  143.63     .06       0  204.26    .045       0
  236.09     .06       0  414.09     .08       0
#XS Ineff= 2 , 0
                           250.9          991.05
Permanent Ineff=
       F       F
Bank Sta=204.26,236.09
XS Rating Curve= 0 ,0
Exp/Cntr(USF)=0,0
Exp/Cntr=0.3,0.1

Type RM Length L Ch R = 1 ,589     ,295.1,289.5,280.1
XS GIS Cut Line= 4
1669436.01237376512136.893018588 1669505.3380225512197.996242836
1669645.76746776512328.4388327831669733.64911222512437.766669485
#Sta/Elev= 30
       0  1067.4    37.6 1050.16    46.3 1045.49    55.1 1041.97      78 1030.25
   100.7 1021.15     110 1016.17   121.4  1007.5   125.8 1004.93   141.1  997.65
   163.4  985.26     170  982.75   174.9  981.85   200.5  981.36  208.23979.0831
   215.4  977.32   228.4  977.66  237.74979.0838   255.7  984.16   261.6  986.65
   276.1  987.85   307.4  988.11   334.7  990.24   344.5  988.27   355.6  988.88
   370.4  988.17   376.6     991   398.4 1007.75   411.8 1016.67   424.3 1023.94
#Mann= 4 ,-1,0
       0      .1       0  208.23    .045       0  237.74      .1       0
  252.41     .06       0
Bank Sta=208.23,237.74
XS Rating Curve= 0 ,0
Exp/Cntr(USF)=0,0
Exp/Cntr=0.3,0.1

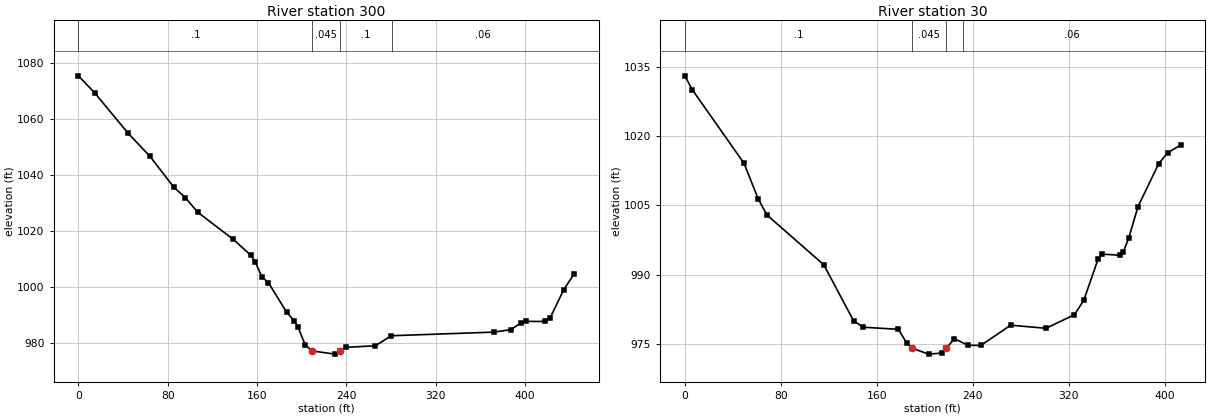
Type RM Length L Ch R = 1 ,300     ,265.4,270,272.3
XS GIS Cut Line= 6
1669180.59720217512373.6330306681669263.09605293512413.852110341
1669337.17037985 512442.398313091669436.50285834512453.947174504
1669506.41282351512492.0734105861669580.70926283512548.500463083
#Sta/Elev= 30
       0 1075.53    14.8 1069.39    44.2 1055.17    64.2 1046.73    85.6 1035.68
    95.9 1031.97   106.9 1026.78   138.6 1017.13   154.3 1011.47   158.5 1009.04
   164.4 1003.65   170.2 1001.66   186.5  991.06   193.4  987.96   196.7  985.77
   203.3  979.26  209.49977.2057   229.7  976.06   234.5977.2064   239.6  978.48
     266  979.04   280.3  982.63     372  983.93   387.3  984.79   396.5  987.21
   401.4  987.77   418.4  987.73   422.5  988.92   434.7  999.06   444.1 1004.74
#Mann= 4 ,-1,0
       0      .1       0  209.49    .045       0   234.5      .1       0
  281.17     .06       0
Bank Sta=209.49,234.5
XS Rating Curve= 0 ,0
Exp/Cntr(USF)=0,0
Exp/Cntr=0.3,0.1

Type RM Length L Ch R = 1 ,30      ,,,
XS GIS Cut Line= 3
1669134.29641926512494.4309489751669209.13445754512648.883921582
1669428.07552695512750.791037528
#Sta/Elev= 30
       0 1033.08     6.4 1030.01    49.4  1014.1    61.1 1006.43    68.4 1002.94
   115.8  992.13   140.7  979.96   148.6   978.6     178  978.15     185   975.1
  189.67974.0157   203.3  972.77   214.2     973  217.93974.0173   224.5  976.13
   235.9  974.69   246.6  974.65   271.5  979.04     301  978.37   324.6  981.32
   332.4  984.44   344.4  993.41     348  994.44   362.5   994.2   365.3   994.9
   369.8  997.88   377.6 1004.74   394.9 1014.07   402.3 1016.41   413.1 1018.07
#Mann= 4 ,-1,0
       0      .1       0  189.67    .045       0  217.93      .1       0
  231.63     .06       0
Bank Sta=189.67,217.93
XS Rating Curve= 0 ,0
Exp/Cntr(USF)=0,0
Exp/Cntr=0.3,0.1
LCMann Table=0

Chan Stop Cuts=-1
Use User Specified Reach Order=0
Composite Channel Slope=5